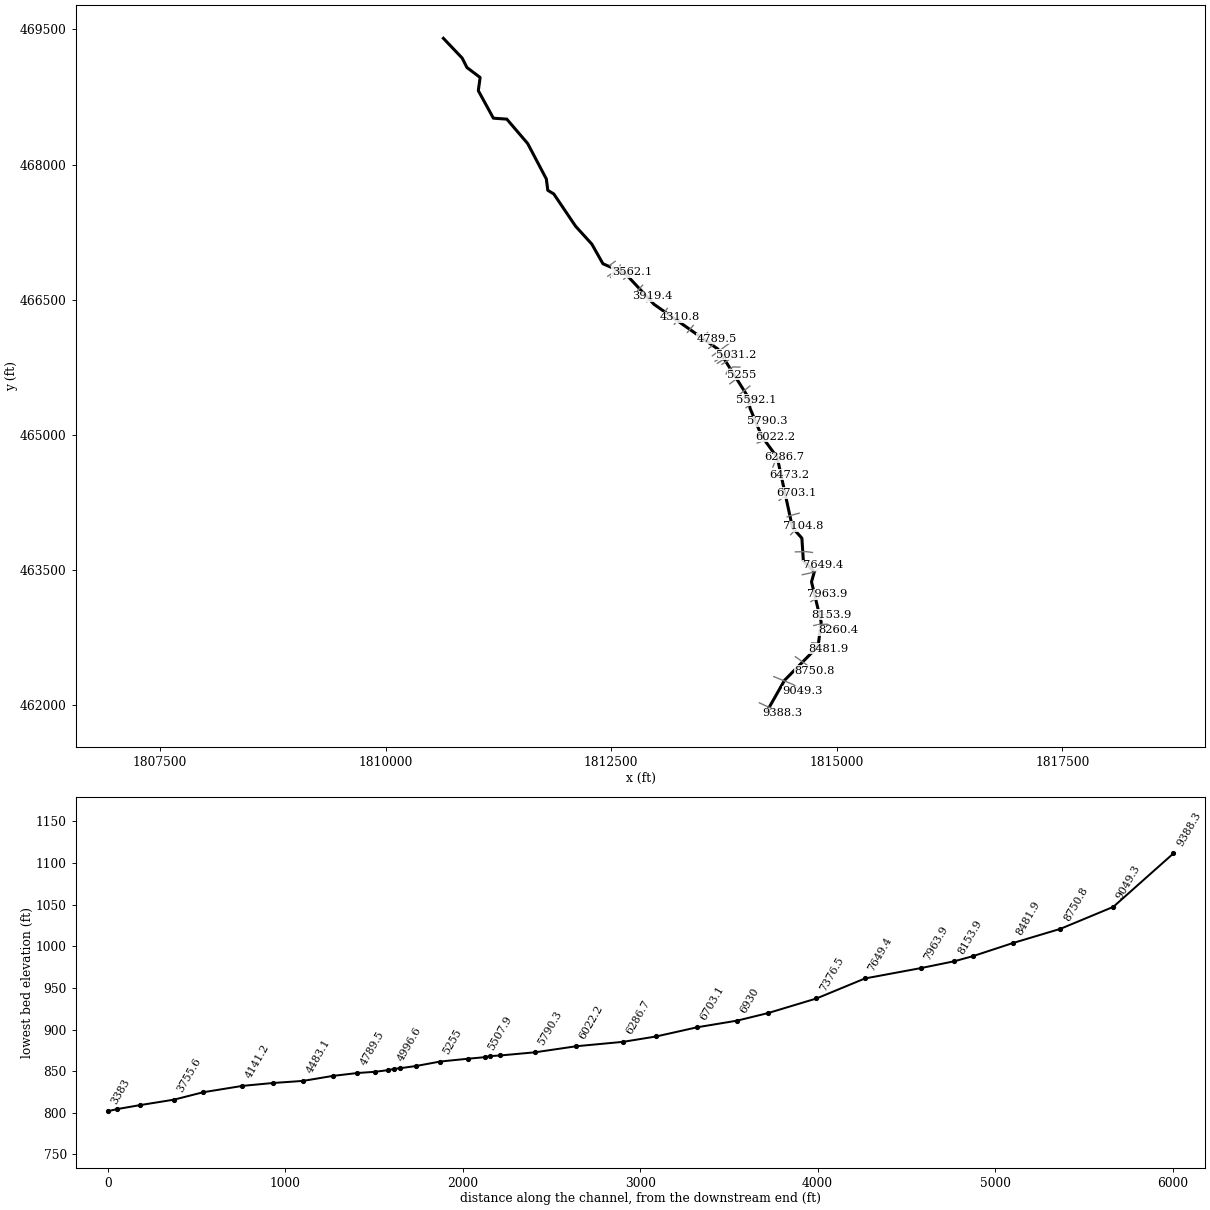
--- GEORGESCK.prj (project) ---

Proj Title=GEORGESCK
Current Plan=p01
Default Exp/Contr=0,0
English Units
Geom File=g01
Flow File=f01
Plan File=p01
BEGIN DESCRIPTION:
END DESCRIPTION:
DSS Export Rating Curves= 0
DSS Export Rating Curve Sorted= 0
DSS Export Volume Flow Curves= 0
DXF OffsetX= 0
DXF OffsetY= 0
DXF ScaleX= 0
DXF ScaleY= 0

--- GEORGESCK.p01 (plan) ---

Plan Title=Floodplain
Program Version=4.00
Geom File=g01
Flow File=f01
K Sum by GR=0
Std Step Tol=0.01
Critical Tol=0.01
Num of Std Step Trials=20
Max Error Tol=0.3
Flow Tol Ratio=0.001
Split Flow NTrial=30
Split Flow Tol=0.02
Split Flow Ratio=0.02
Log Output Level=0
Friction Slope Method=1
Unsteady Friction Slope Method=2
Unsteady Bridges Friction Slope Method=1
Global Log Level=0
CheckData=False
Run HTab=0
Run UNet=0
Run PostProcess=0
UNET Theta=0
UNET Theta Warmup=0
UNET ZTol=0
UNET ZSATol=0
UNET MxIter=0
UNET MaxInSteps=0
UNET DtIC=0
UNET DtMin=0
UNET MaxCRTS=0
UNET WFStab=0
UNET SFStab=0
UNET WFX=0
UNET SFX=0
UNET DSS MLevel=0
UNET DZMax Abort=0
UNET Convert EG Bridges=0
UNET Use Existing IB Tables=0
UNET Froude Limit=0
UNET Froude Power=0
Write IC File=0
Echo Input=False
Echo Output=False
Write Detailed=0

--- GEORGESCK.f01 (steady flow) ---

Flow Title=NFF Regression Equation
Program Version=4.10
Number of Profiles= 1
Profile Names=P100yr
River Rch & RM=GEORGESCK,Main            ,9388.3
      59
River Rch & RM=GEORGESCK,Main            ,8260.4
     190
River Rch & RM=GEORGESCK,Main            ,7649.4
     227
River Rch & RM=GEORGESCK,Main            ,6286.7
     292
River Rch & RM=GEORGESCK,Main            ,5790.3
     342
River Rch & RM=GEORGESCK,Main            ,4649.8
     496
River Rch & RM=GEORGESCK,Main            ,2852.1
     547
River Rch & RM=GEORGESCK,Main            ,775.7
     585
Boundary for River Rch & Prof#=GEORGESCK,Main            , 1
Up Type= 0
Dn Type= 1
Dn Known WS=721.2
DSS Import GetInterval= 0
DSS Import GetPeak= 0
DSS Import FillOption= 0

--- GEORGESCK.g01 (geometry) ---

Geom Title=USGS 10m DEM
Program Version=4.10

River Reach=GEORGESCK       ,Main
Reach XY= 30
     1814231.611      461939.805     1814420.586       462274.05
     1814793.071      462652.387     1814826.836      462921.967
     1814719.865      463367.346     1814751.142      463479.606
     1814629.587      463600.419     1814613.224      463852.537
     1814509.475      463968.495      1814340.09      464747.989
     1814168.633      464983.825     1814038.543      465295.079
     1814021.189      465413.368     1813683.781      465951.134
     1812974.552      466449.117      1812656.09      466791.368
     1812408.694      466899.441     1812286.298      467116.889
     1812106.323      467315.263     1811864.423       467674.18
     1811798.017      467714.545     1811781.805      467840.698
     1811575.073      468234.013     1811343.817      468504.891
     1811195.152      468515.326     1811028.111      468821.007
     1811048.243      468967.296     1810902.184      469077.826
     1810849.314      469182.682     1810641.414      469401.866

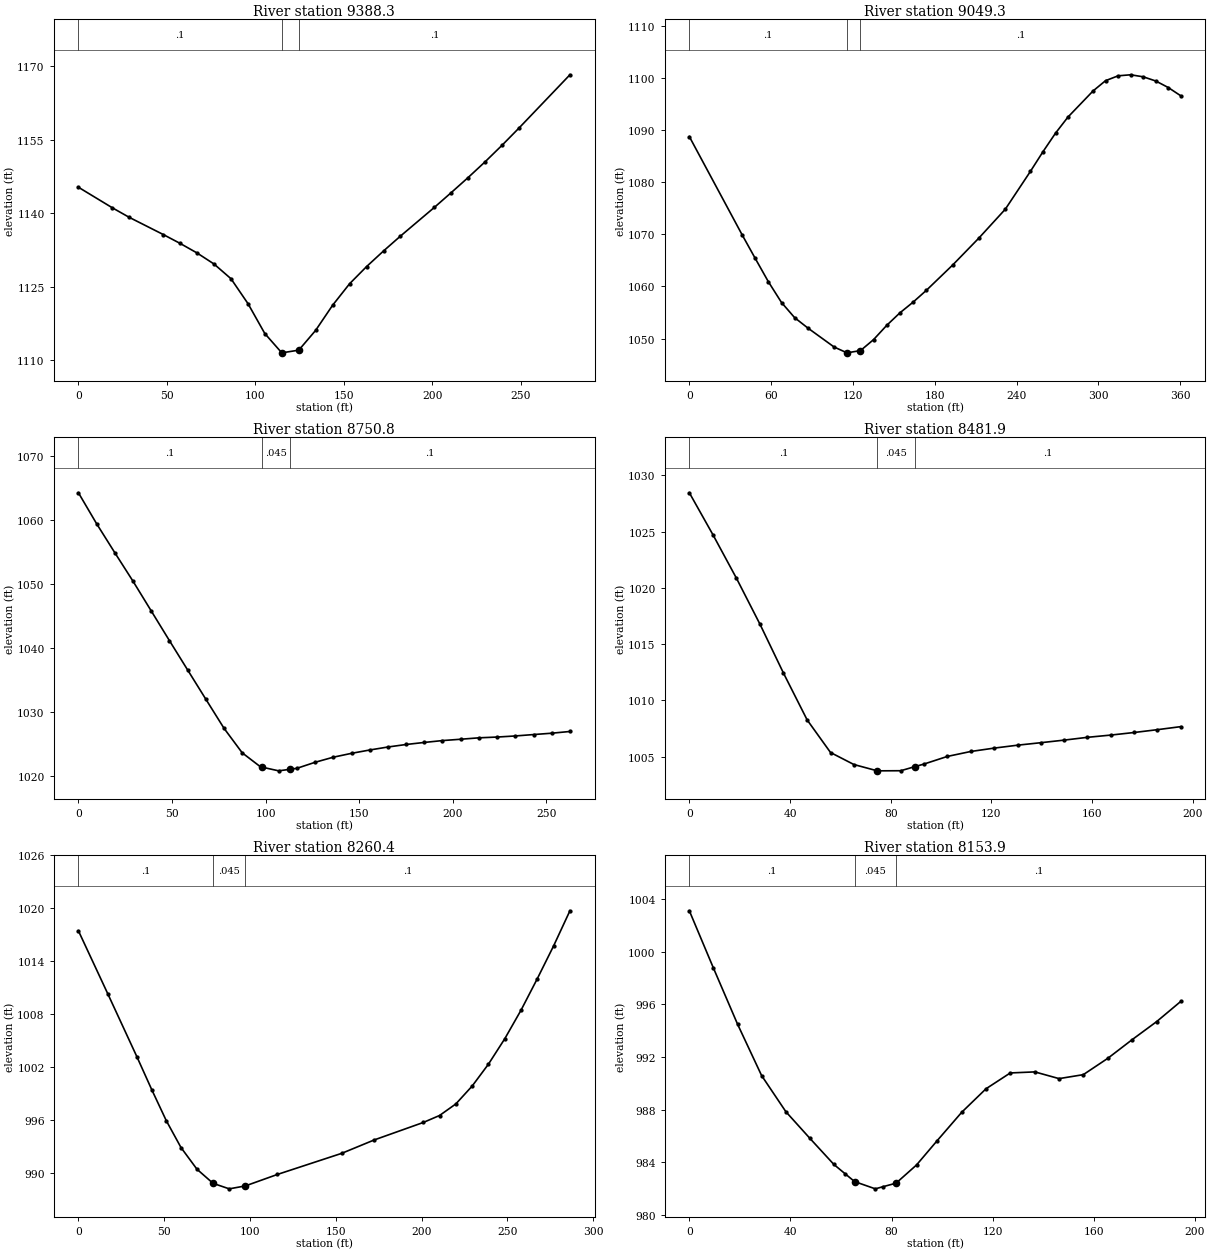
Type RM Length L Ch R = 1 ,9388.3  ,337.8,339,340.2
XS GIS Cut Line= 2
     1814141.848      462024.479     1814393.584      461907.291
#Sta/Elev= 25
       0 1145.29    19.2 1141.08    28.7 1139.14    47.9 1135.63    57.4 1133.82
      67 1131.86    76.6  1129.6    86.2 1126.59    95.8  1121.5   105.3 1115.39
   114.9 1111.44   124.5 1111.99     134 1116.02   143.6 1121.16   153.2 1125.56
   162.8 1129.07   172.4 1132.27   181.9 1135.29   201.1 1141.17   210.6 1144.18
   220.2 1147.28   229.8  1150.5   239.4 1153.89     249 1157.42   277.7 1168.28
#Mann= 3 , 0 , 0
       0      .1       0   114.9    .045       0   124.5      .1       0
Bank Sta=114.9,124.5
XS Rating Curve= 0 ,0
Exp/Cntr=0.3,0.1

Type RM Length L Ch R = 1 ,9049.3  ,304,298.5,293
XS GIS Cut Line= 3
     1814302.439      462315.277     1814516.833      462227.478
     1814621.709      462152.822
#Sta/Elev= 30
       0 1088.75    38.6 1069.96    48.3 1065.39    57.9 1060.93    67.6 1056.92
    77.2 1054.02    86.9 1052.03   106.2 1048.38   115.6 1047.27   125.5  1047.7
   135.1 1049.81   144.8 1052.56   154.4 1054.94   164.1    1057   173.8 1059.26
   193.1 1064.12   212.4 1069.31   231.7 1074.83   250.1 1082.08   259.3 1085.85
   268.5 1089.41   277.6 1092.49     296  1097.5   305.2 1099.48   314.4 1100.41
   323.6 1100.61   332.8 1100.22     342 1099.42   351.2 1098.16   360.4 1096.57
#Mann= 3 , 0 , 0
       0      .1       0   115.6    .045       0   125.5      .1       0
Bank Sta=115.6,125.5
XS Rating Curve= 0 ,0
Exp/Cntr=0.3,0.1

Type RM Length L Ch R = 1 ,8750.8  ,265.3,268.9,272.2
XS GIS Cut Line= 2
     1814541.154      462536.632     1814753.828      462382.552
#Sta/Elev= 30
       0 1064.22     9.7  1059.4    19.4 1054.89    29.2 1050.41    38.9 1045.79
    48.6 1041.17    58.4 1036.56    68.1 1032.01    77.8 1027.48    87.5 1023.66
    97.3 1021.47      98 1021.43     107 1020.85     113 1021.09   116.7 1021.24
   126.4 1022.18   136.2 1022.98   145.9 1023.58   155.6  1024.1   165.4 1024.57
   175.1 1024.96   184.8 1025.28   194.5 1025.57   204.3 1025.78     214    1026
   223.7 1026.12   233.4 1026.29   243.2 1026.51   252.9 1026.72   262.6 1026.99
#Mann= 3 , 0 , 0
       0      .1       0      98    .045       0     113      .1       0
Bank Sta=98,113
XS Rating Curve= 0 ,0
Exp/Cntr=0.3,0.1

Type RM Length L Ch R = 1 ,8481.9  ,210.1,221.6,232.9
XS GIS Cut Line= 3
     1814723.446      462691.146     1814779.435      462687.239
     1814903.133      462623.437
#Sta/Elev= 23
       0 1028.46     9.4 1024.72    18.7 1020.87    28.1 1016.76    37.4 1012.43
    46.8 1008.27    56.1 1005.37    65.4  1004.3    74.7 1003.74      84 1003.75
    89.7 1004.12    93.2 1004.34   102.5 1005.02   111.8 1005.46   121.1 1005.76
   130.4 1006.02   139.6 1006.24   148.9 1006.47   158.2 1006.72   167.5 1006.92
   176.8 1007.15     186  1007.4   195.3 1007.67
#Mann= 3 , 0 , 0
       0      .1       0    74.7    .045       0    89.7      .1       0
Bank Sta=74.7,89.7
XS Rating Curve= 0 ,0
Exp/Cntr=0.3,0.1

Type RM Length L Ch R = 1 ,8260.4  ,99.7,106.5,110.7
XS GIS Cut Line= 4
     1814744.279      462882.552     1814802.873      462894.271
     1814896.623      462896.875     1815012.508      462831.771
#Sta/Elev= 23
       0 1017.44    17.1 1010.32    34.2 1003.14    42.7  999.48    51.2  995.96
    59.8  992.91    69.1  990.46    78.5  988.86    87.9  988.24    97.3  988.57
     116  989.87   153.5  992.26   172.5  993.78     201  995.75   210.5  996.54
     220  997.85   229.5  999.87     239 1002.35   248.5 1005.22     258 1008.46
   267.5 1012.03     277 1015.74   286.5 1019.71
#Mann= 3 , 0 , 0
       0      .1       0    78.5    .045       0    97.3      .1       0
Bank Sta=78.5,97.3
XS Rating Curve= 0 ,0
Exp/Cntr=0.3,0.1

Type RM Length L Ch R = 1 ,8153.9  ,186.2,189.9,192.9
XS GIS Cut Line= 4
      1814755.13      462973.264     1814806.605      462998.308
     1814846.536      463006.989      1814942.89      463004.385
#Sta/Elev= 24
       0 1003.09     9.5  998.76    19.1  994.48    28.6  990.59    38.2  987.85
    47.7  985.83    57.2  983.85    61.6  983.15    65.4  982.55    73.6     982
    76.6  982.16    81.8  982.43    89.9  983.81    98.1  985.66   107.8  987.81
   117.4  989.59     127  990.79   136.7  990.87   146.3  990.36   155.9  990.66
   165.6   991.9   175.2  993.31   184.9  994.68   194.5  996.22
#Mann= 3 , 0 , 0
       0      .1       0    65.4    .045       0    81.8      .1       0
Bank Sta=65.4,81.8
XS Rating Curve= 0 ,0
Exp/Cntr=0.3,0.1

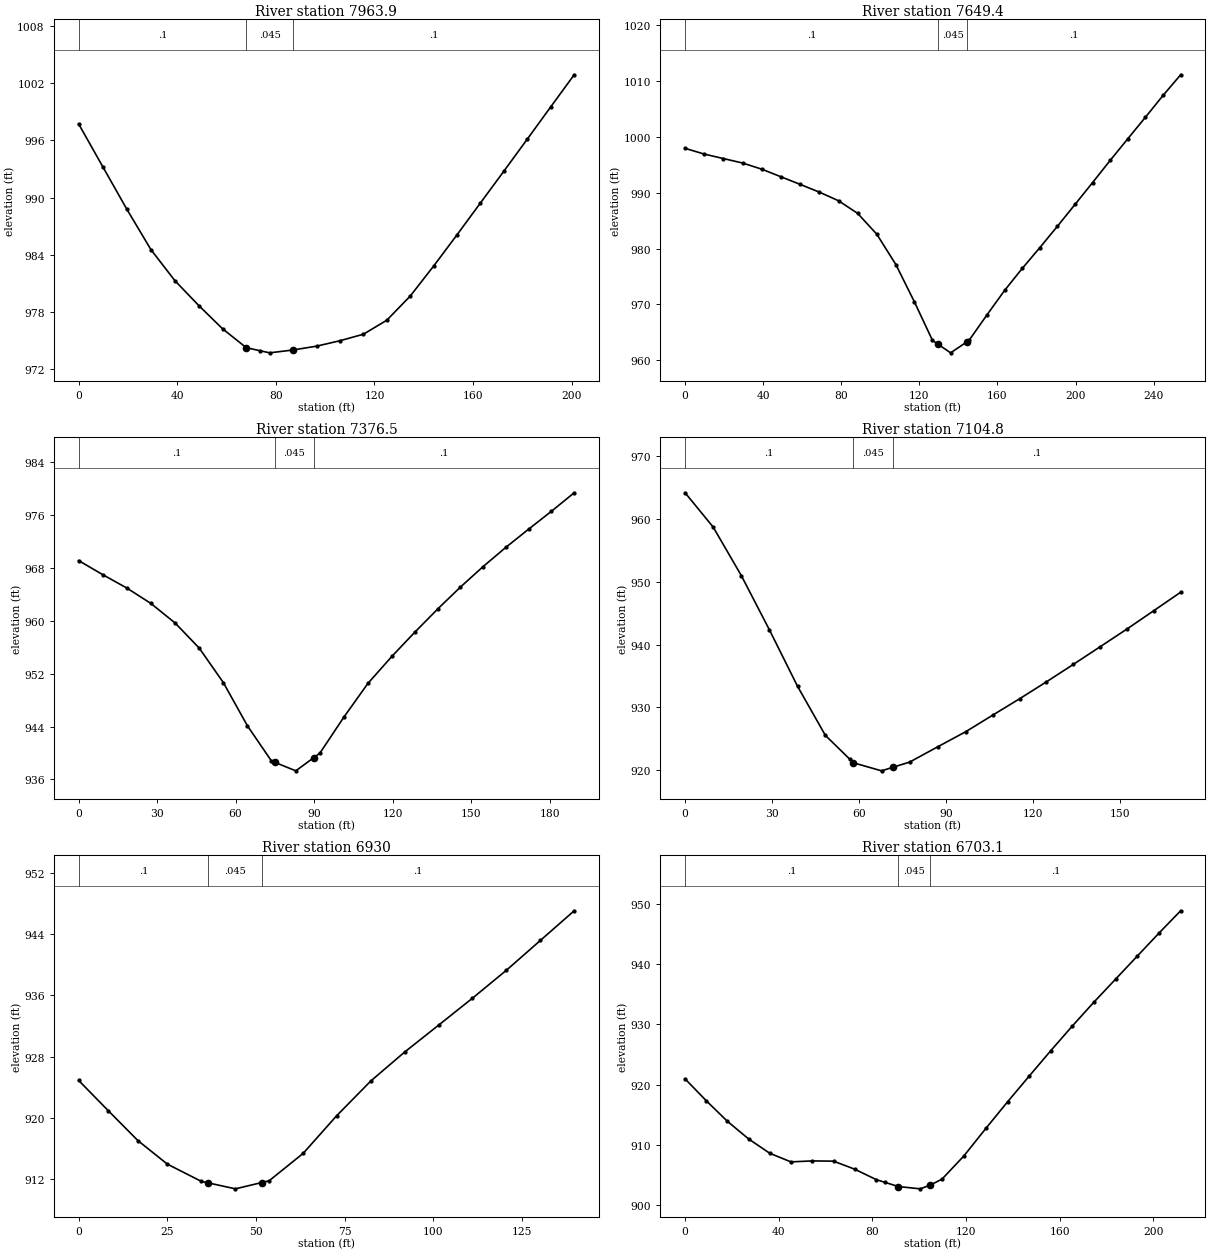
Type RM Length L Ch R = 1 ,7963.9  ,316.3,314.5,317
XS GIS Cut Line= 3
     1814713.029      463148.177     1814762.508      463179.427
     1814896.623      463227.604
#Sta/Elev= 23
       0  997.73     9.8  993.24    19.5  988.81    29.3  984.56      39  981.31
    48.8  978.67    58.4  976.25      68  974.27    73.4  973.96    77.5  973.73
      87  974.03    96.5  974.43     106     975   115.5  975.68     125  977.15
   134.5  979.68     144  982.83   153.5  986.11     163  989.45   172.5  992.78
     182  996.14   191.5  999.52     201 1002.88
#Mann= 3 , 0 , 0
       0      .1       0      68    .045       0      87      .1       0
Bank Sta=68,87
XS Rating Curve= 0 ,0
Exp/Cntr=0.3,0.1

Type RM Length L Ch R = 1 ,7649.4  ,281.5,272.8,262
XS GIS Cut Line= 4
     1814617.977      463446.354     1814723.446      463469.791
     1814766.414      463488.021     1814843.237      463550.521
#Sta/Elev= 30
       0  997.97     9.8  996.94    19.6  996.14    29.5  995.33    39.3  994.23
    49.1  992.87    58.9  991.51    68.8  990.11    78.6  988.57    88.4   986.3
    98.2  982.56     108   977.1   117.4  970.47   126.7  963.53   129.6  962.83
     136   961.3   144.6  963.33   145.4  963.52   154.7  968.15   163.7  972.52
   172.7  976.45   181.7  980.17   190.7     984   199.7  987.91   208.7  991.83
   217.7   995.8   226.7  999.67   235.8 1003.56   244.8 1007.46   253.8 1011.16
#Mann= 3 , 0 , 0
       0      .1       0   129.6    .045       0   144.6      .1       0
Bank Sta=129.6,144.6
XS Rating Curve= 0 ,0
Exp/Cntr=0.3,0.1

Type RM Length L Ch R = 1 ,7376.5  ,252.6,271.7,290.7
XS GIS Cut Line= 3
     1814541.154       463700.26     1814660.946      463702.864
     1814729.956       463693.75
#Sta/Elev= 24
       0   969.1     9.2  966.97    18.4  964.95    27.6  962.62    36.9  959.65
    46.1  955.86    55.3  950.65    64.5  944.12    73.7  938.79    74.9   938.6
      83   937.3    89.9   939.3    92.2  939.97   101.4  945.43   110.6  950.54
   119.8  954.64   128.5  958.27   137.2  961.76   145.9  965.08   154.6  968.19
   163.3   971.1     172  973.85   180.7  976.55   189.4  979.35
#Mann= 3 , 0 , 0
       0      .1       0    74.9    .045       0    89.9      .1       0
Bank Sta=74.9,89.9
XS Rating Curve= 0 ,0
Exp/Cntr=0.3,0.1

Type RM Length L Ch R = 1 ,7104.8  ,187.4,174.8,161.2
XS GIS Cut Line= 3
     1814489.071      463890.364     1814552.873      463963.281
     1814623.185      463986.718
#Sta/Elev= 21
       0  964.21     9.7  958.73    19.4     951    29.1  942.34    38.8  933.34
    48.4  925.51    56.8  921.72    58.1  921.13    67.8  919.85    71.8  920.43
    77.5  921.25    87.2  923.69    96.9  926.11   106.2  928.75   115.4  931.34
   124.7  934.05     134  936.84   143.2  939.64   152.5  942.48   161.7  945.39
     171  948.34
#Mann= 3 , 0 , 0
       0      .1       0    58.1    .045       0    71.8      .1       0
Bank Sta=58.1,71.8
XS Rating Curve= 0 ,0
Exp/Cntr=0.3,0.1

Type RM Length L Ch R = 1 ,6930    ,223.9,226.9,230.2
XS GIS Cut Line= 3
     1814450.008      464088.281     1814472.143         464100.
     1814582.821      464129.948
#Sta/Elev= 18
       0  924.88     8.4  920.91    16.7  917.03      25  913.96    34.6   911.7
    36.6   911.5    44.2  910.73    51.6  911.55    53.7  911.78    63.3  915.36
    72.8   920.3    82.4  924.82    91.9  928.58   101.5   932.1     111   935.6
   120.6  939.26   130.2  943.16   139.7  947.02
#Mann= 3 , 0 , 0
       0      .1       0    36.6    .045       0    51.6      .1       0
Bank Sta=36.6,51.6
XS Rating Curve= 0 ,0
Exp/Cntr=0.3,0.1

Type RM Length L Ch R = 1 ,6703.1  ,235.8,229.9,223.7
XS GIS Cut Line= 4
     1814361.466      464271.875     1814418.758      464316.146
     1814478.654      464342.187     1814551.571      464353.906
#Sta/Elev= 26
       0  920.95       9  917.34    18.1  913.89    27.2  910.95    36.2  908.58
    45.2  907.16    54.3  907.32    63.4  907.28    72.4  905.95    81.7   904.2
    85.4  903.75    91.1  903.06   100.4  902.68  104.74  903.32   109.7  904.29
     119  908.13   128.4  912.71   137.7  917.14     147  921.45   156.2  925.66
   165.4  929.76   174.6  933.72   183.9  937.56   193.1  941.36   202.3  945.16
   211.6  948.89
#Mann= 3 , 0 , 0
       0      .1       0    91.1    .045       0  104.74      .1       0
Bank Sta=91.1,104.74
XS Rating Curve= 0 ,0
Exp/Cntr=0.3,0.1

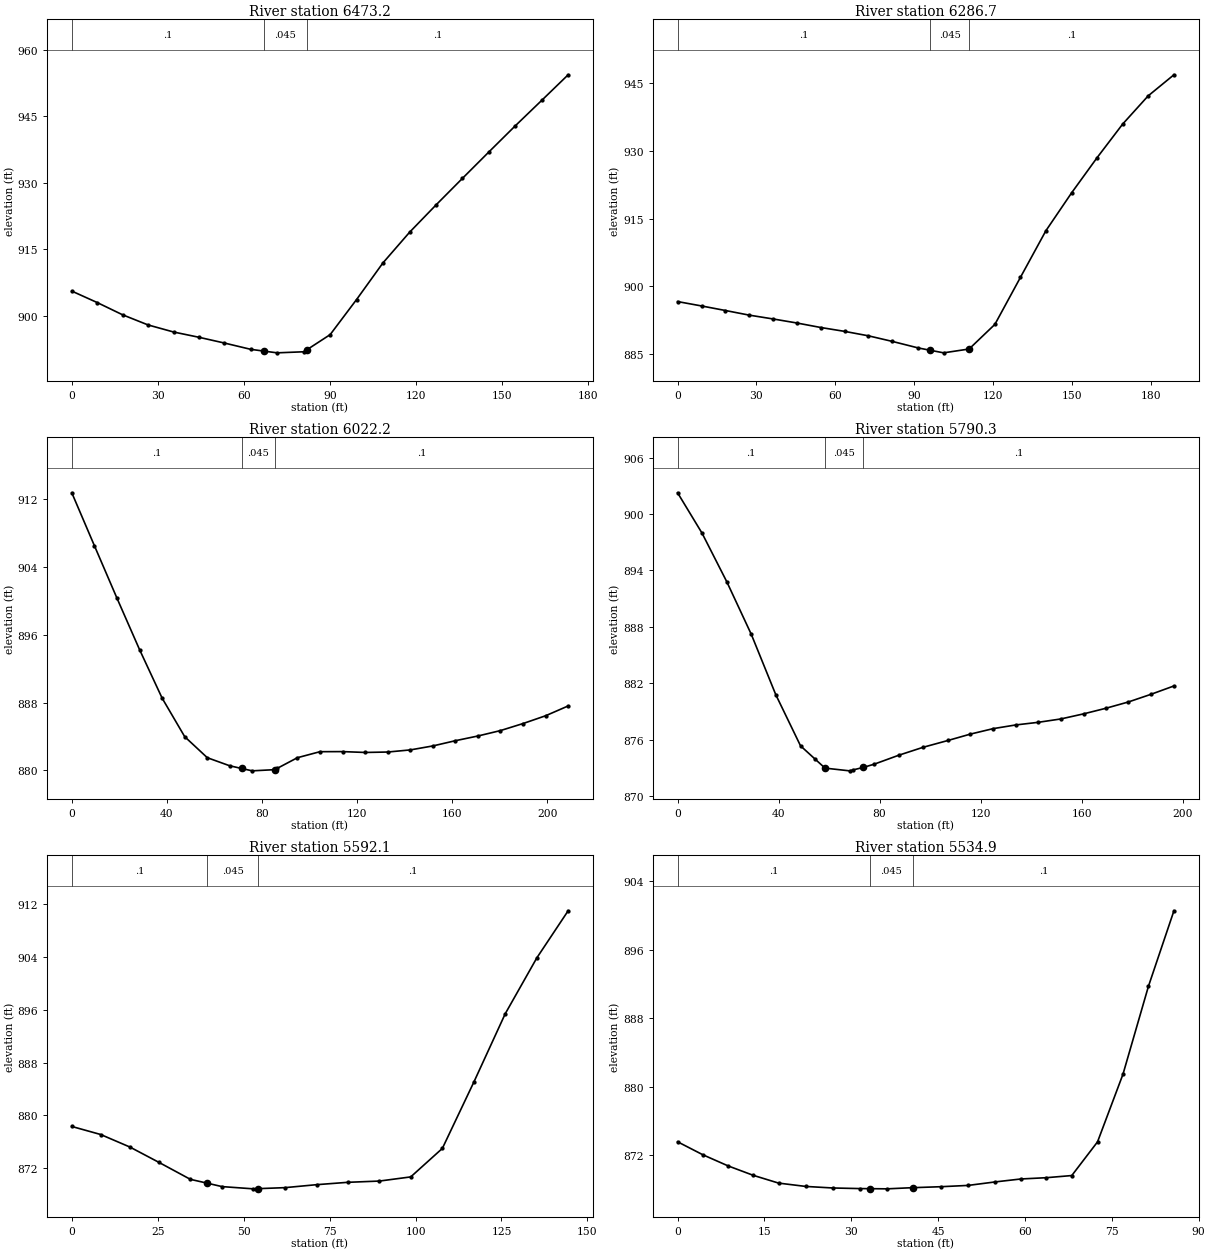
Type RM Length L Ch R = 1 ,6473.2  ,182.8,186.4,190.1
XS GIS Cut Line= 3
     1814308.081      464520.573      1814357.56      464540.104
      1814476.05      464558.333
#Sta/Elev= 22
       0  905.61     8.9  903.02    17.7  900.28    26.6  897.99    35.5   896.4
    44.3  895.22    53.2  893.92    62.4   892.5      67   892.1    71.6  891.71
    80.9  891.95      82  892.41    90.1  895.81    99.3   903.7   108.5  911.95
   117.8  918.86     127  924.99   136.2  930.97   145.4   936.9   154.6  942.78
   163.9  948.56   173.1  954.31
#Mann= 3 , 0 , 0
       0      .1       0      67    .045       0      82      .1       0
Bank Sta=67,82
XS Rating Curve= 0 ,0
Exp/Cntr=0.3,0.1

Type RM Length L Ch R = 1 ,6286.7  ,263.6,264.5,264.7
XS GIS Cut Line= 3
     1814291.154      464641.666     1814322.404      464717.187
     1814423.966      464751.041
#Sta/Elev= 23
       0  896.61     9.1  895.64    18.2  894.63    27.2  893.61    36.3  892.76
    45.4  891.86    54.5  890.86    63.6     890    72.6  889.02    81.7  887.78
    91.5  886.34      96  885.83   101.2  885.25   110.9   886.1     111  886.16
   120.7  891.56   130.4  901.96   140.1  912.31   149.9  920.72   159.6  928.52
   169.3  935.94     179  942.19   188.8  946.86
#Mann= 3 , 0 , 0
       0      .1       0      96    .045       0     111      .1       0
Bank Sta=96,111
XS Rating Curve= 0 ,0
Exp/Cntr=0.3,0.1

Type RM Length L Ch R = 1 ,6022.2  ,232.3,231.9,231.4
XS GIS Cut Line= 2
     1814117.977      464908.593     1814314.591      464978.906
#Sta/Elev= 25
       0  912.76     9.5  906.52      19  900.32    28.5  894.25      38  888.52
    47.5  883.97      57  881.49    66.4  880.54    71.4  880.22    75.9  879.94
    85.4  880.08    86.4  880.23    94.9  881.49   104.4   882.2   113.9  882.21
   123.4  882.11   132.9  882.16   142.4  882.41   151.9  882.88   161.4   883.5
   170.8  884.05   180.3  884.69   189.8  885.52   199.3  886.44   208.8   887.6
#Mann= 3 , 0 , 0
       0      .1       0    71.4    .045       0    85.4      .1       0
Bank Sta=71.4,85.4
XS Rating Curve= 0 ,0
Exp/Cntr=0.3,0.1

Type RM Length L Ch R = 1 ,5790.3  ,189,198.2,204.7
XS GIS Cut Line= 3
     1814043.758      465128.646     1814145.321        465162.5
     1814233.862      465149.479
#Sta/Elev= 25
       0  902.26     9.7  897.96    19.5  892.79    29.2   887.2    38.9  880.78
    48.7  875.34    54.5  873.92    58.4  872.97    68.1  872.68    69.5  872.78
   73.52  873.04    77.9  873.39    87.6  874.34    97.3  875.19   107.1  875.91
     116  876.59     125  877.17   133.9  877.56   142.8  877.84   151.8   878.2
   160.8  878.74   169.7  879.34   178.6  880.01   187.6  880.83   196.6  881.71
#Mann= 3 , 0 , 0
       0      .1       0    58.4    .045       0   73.52      .1       0
Bank Sta=58.4,73.52
XS Rating Curve= 0 ,0
Exp/Cntr=0.3,0.1

Type RM Length L Ch R = 1 ,5592.1  ,94.7,57.3,20.1
XS GIS Cut Line= 3
     1813994.279      465300.521     1814014.244      465316.146
      1814109.73      465387.326
#Sta/Elev= 19
       0   878.3     8.4  877.08    16.9  875.18    25.4  872.84    34.5  870.28
    39.3  869.71    43.7  869.18    52.8  868.84    54.3  868.87      62  869.02
    71.2  869.47    80.3  869.83    89.5  870.02    98.6  870.65   107.8  874.97
     117  885.07   126.1   895.4   135.3  903.88   144.4  911.01
#Mann= 3 , 0 , 0
       0      .1       0    39.3    .045       0    54.3      .1       0
Bank Sta=39.3,54.3
XS Rating Curve= 0 ,0
Exp/Cntr=0.3,0.1

Type RM Length L Ch R = 1 ,5534.9  ,34.6,27,30.3
XS GIS Cut Line= 4
     1813958.689      465391.666     1813987.334      465411.632
     1814039.418      465357.812     1814087.161      465396.875
#Sta/Elev= 22
       0  873.57    4.35  872.06    8.75  870.75    13.1  869.65   17.45  868.75
   22.15  868.36    26.8  868.18    31.5  868.11    33.2   868.1    36.2  868.08
    40.7  868.22   40.85  868.22   45.55  868.33    50.2  868.48    54.9  868.89
    59.3  869.23    63.7  869.38    68.1  869.63   72.55  873.56   76.95  881.46
   81.35  891.72   85.75  900.52
#Mann= 3 , 0 , 0
       0      .1       0    33.2    .045       0    40.7      .1       0
Bank Sta=33.2,40.7
XS Rating Curve= 0 ,0
Skew Angle= 60
Exp/Cntr=0.3,0.1

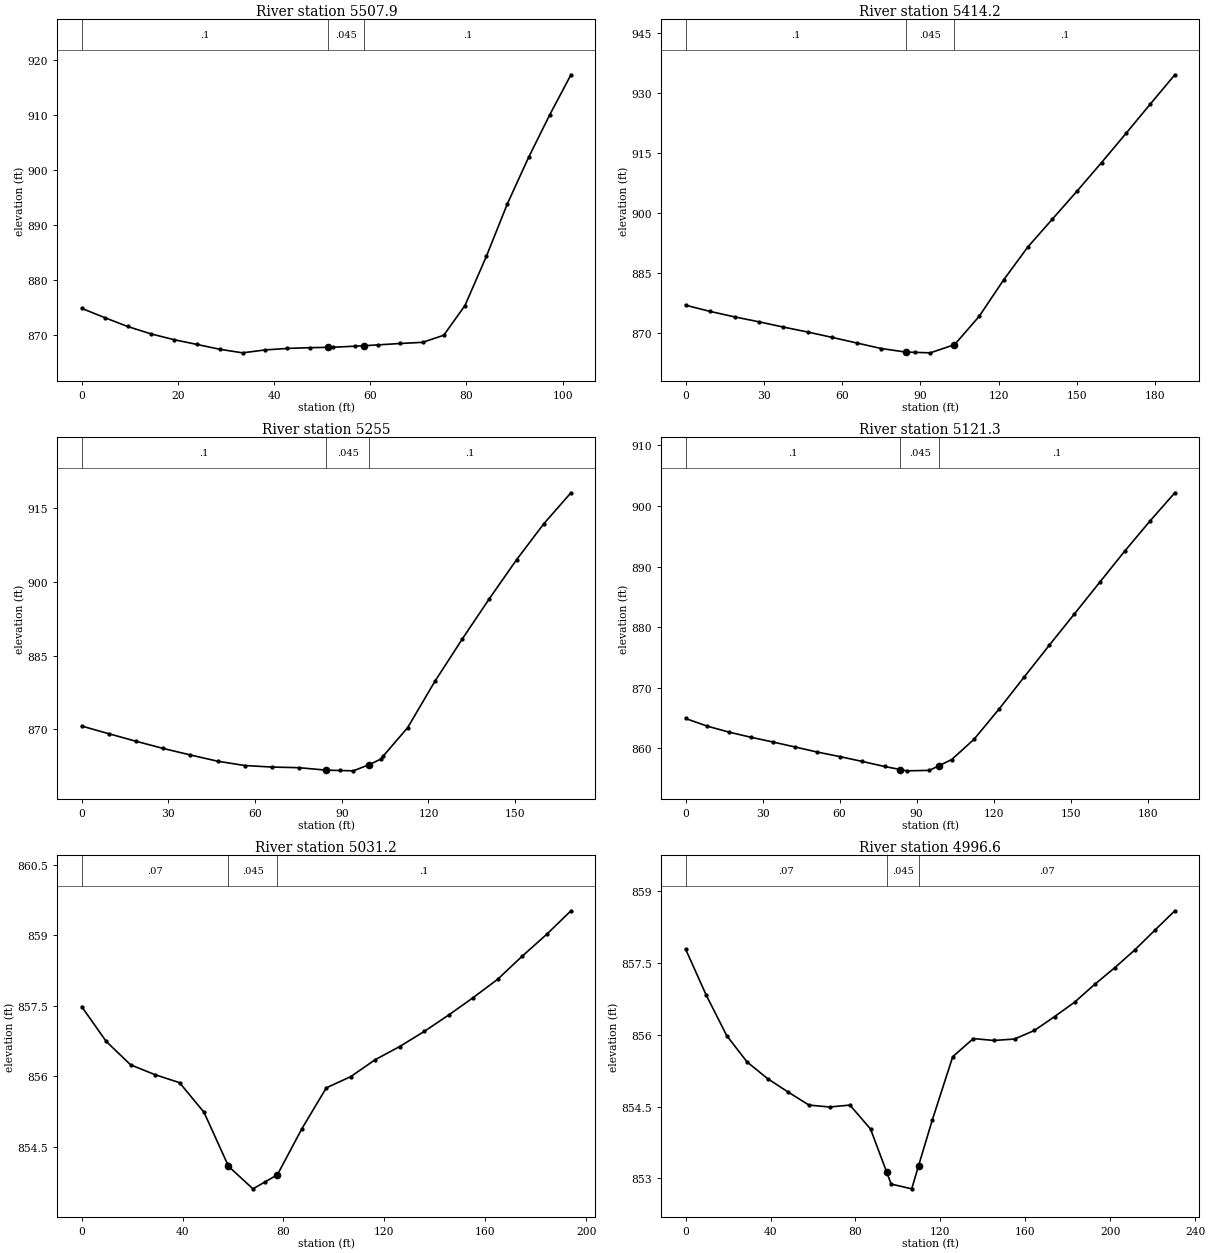
Type RM Length L Ch R = 1 ,5507.9  ,47.4,93.7,129.8
XS GIS Cut Line= 4
     1813934.383      465402.951     1813989.939      465440.277
     1814042.022      465386.458     1814089.765      465425.521
#Sta/Elev= 25
       0  874.93     4.8  873.23    9.55  871.63   14.35   870.3    19.1  869.25
    23.9  868.38    28.7  867.49   33.45  866.84   38.15  867.37    42.8  867.64
    47.5  867.78   51.25  867.84    52.2  867.85   56.85  868.05   58.75  868.14
   61.55  868.28   66.25  868.54    70.9  868.75    75.3  870.04    79.7  875.43
   84.15  884.36   88.55  893.98   92.95  902.39   97.35  910.13  101.75  917.38
#Mann= 3 , 0 , 0
       0      .1       0   51.25    .045       0   58.75      .1       0
Bank Sta=51.25,58.75
XS Rating Curve= 0 ,0
Skew Angle= 60
Exp/Cntr=0.3,0.1

Type RM Length L Ch R = 1 ,5414.2  ,160,159.2,158.3
XS GIS Cut Line= 2
     1813891.848      465422.916     1814036.814       465541.84
#Sta/Elev= 23
       0  876.91     9.4  875.36    18.8  873.99    28.1  872.76    37.5  871.44
    46.9  870.19    56.2  868.86    65.6  867.46      75  866.08    84.4  865.19
    87.8  865.12    93.8     865   102.8  866.99   103.1  867.06   112.5  874.11
   121.9  883.25   131.2   891.5   140.6  898.46     150  905.42   159.4  912.57
   168.8  919.88   178.1  927.21   187.5  934.53
#Mann= 3 , 0 , 0
       0      .1       0    84.4    .045       0   102.8      .1       0
Bank Sta=84.4,102.8
XS Rating Curve= 0 ,0
Exp/Cntr=0.3,0.1

Type RM Length L Ch R = 1 ,5255    ,135.7,133.7,131.4
XS GIS Cut Line= 2
     1813814.591      465566.146     1813950.008      465667.708
#Sta/Elev= 22
       0  870.67     9.4  869.11    18.8  867.58    28.2  866.12    37.6   864.8
      47  863.53    56.4  862.65    65.8  862.34    75.2  862.21    84.6  861.71
    89.4  861.64      94  861.57   99.49  862.83   103.4  863.92   104.4  864.61
   112.8  870.36   122.2  879.74   131.7  888.37   141.1  896.59   150.5  904.49
   159.9  911.78   169.3  918.08
#Mann= 3 , 0 , 0
       0      .1       0    84.6    .045       0   99.49      .1       0
Bank Sta=84.6,99.49
XS Rating Curve= 0 ,0
Exp/Cntr=0.3,0.1

Type RM Length L Ch R = 1 ,5121.3  ,89.5,90.1,91
XS GIS Cut Line= 4
     1813773.619      465675.392     1813796.189      465721.399
     1813848.272      465753.517     1813926.397      465751.781
#Sta/Elev= 24
       0  864.92     8.5  863.65    17.1  862.65    25.6  861.81    34.2  861.02
    42.7  860.21    51.2  859.39      60  858.64    68.7  857.84    77.5     857
    83.7  856.49    86.2  856.28      95  856.36    98.7  857.12   103.7  858.15
   112.4   861.5   122.2  866.52     132  871.81   141.7  877.02   151.5  882.19
   161.3  887.38     171   892.5   180.8  897.45   190.6  902.17
#Mann= 3 , 0 , 0
       0      .1       0    83.7    .045       0    98.7      .1       0
Bank Sta=83.7,98.7
XS Rating Curve= 0 ,0
Exp/Cntr=0.3,0.1

Type RM Length L Ch R = 1 ,5031.2  ,35.4,34.6,33.7
XS GIS Cut Line= 2
     1813727.786      465782.291     1813889.244       465889.93
#Sta/Elev= 23
       0  857.48     9.7  856.74    19.4  856.24    29.1  856.03    38.8  855.86
    48.5  855.23    57.8  854.13    58.2  854.08    67.9   853.6    72.8  853.75
    77.6   853.9    87.3  854.88      97  855.75   106.7  855.99   116.4  856.35
   126.1  856.63   135.8  856.95   145.5   857.3   155.2  857.67   164.9  858.06
   174.6  858.55   184.4  859.02     194  859.52
#Mann= 3 , 0 , 0
       0     .07       0    58.2    .045       0    77.6      .1       0
Bank Sta=58.2,77.6
XS Rating Curve= 0 ,0
Exp/Cntr=0.3,0.1

Type RM Length L Ch R = 1 ,4996.6  ,32.6,32.5,32.4
XS GIS Cut Line= 3
     1813676.397      465794.315     1813808.515      465875.173
     1813873.619      465913.368
#Sta/Elev= 27
       0  857.79     9.7  856.83    19.4  855.98      29  855.43    38.7  855.08
    48.4   854.8    58.1  854.53    67.8  854.49    77.4  854.53    87.1  854.03
    94.7  853.13    96.8  852.88   106.5  852.78   109.7  853.26   116.2  854.22
   125.8  855.54   135.5  855.92   145.2  855.88   154.9  855.91   164.3  856.09
   173.8  856.38   183.2  856.68   192.6  857.05   202.1   857.4   211.5  857.77
   220.9  858.18   230.4  858.59
#Mann= 3 , 0 , 0
       0     .07       0    94.7    .045       0   109.7     .07       0
Bank Sta=94.7,109.7
XS Rating Curve= 0 ,0
Exp/Cntr=0.3,0.1

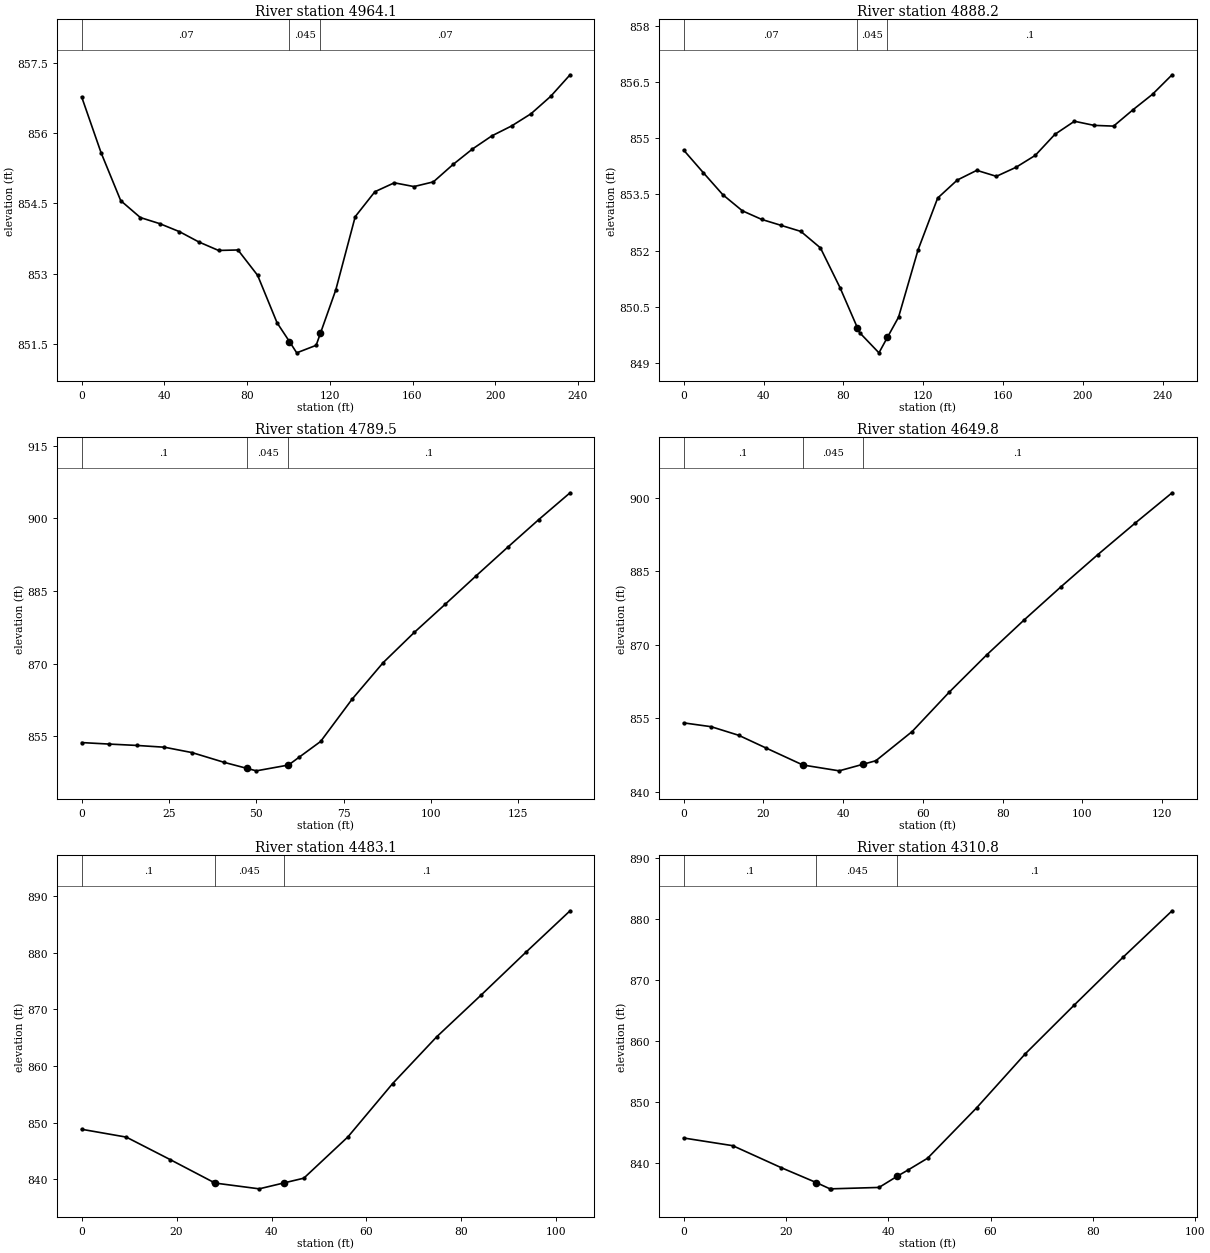
Type RM Length L Ch R = 1 ,4964.1  ,73.8,75.9,77.9
XS GIS Cut Line= 3
     1813651.223      465816.885      1813788.55      465900.347
     1813853.654      465938.541
#Sta/Elev= 28
       0  856.77     9.4  855.58    18.9  854.56    28.4   854.2    37.8  854.07
    47.3   853.9    56.7  853.68    66.2   853.5    75.6  853.51    85.1  852.97
    94.5  851.96   100.5  851.56     104  851.32   113.4  851.48   115.5  851.74
   122.9  852.66   132.3  854.22   141.8  854.75   151.2  854.94   160.7  854.86
   170.1  854.96   179.6  855.33     189  855.66   198.4  855.94   207.9  856.15
   217.3  856.41   226.8  856.78   236.2  857.24
#Mann= 3 , 0 , 0
       0     .07       0   100.5    .045       0   115.5     .07       0
Bank Sta=100.5,115.5
XS Rating Curve= 0 ,0
Exp/Cntr=0.3,0.1

Type RM Length L Ch R = 1 ,4888.2  ,94.3,98.7,104.7
XS GIS Cut Line= 2
     1813621.015      465876.909     1813818.064      466021.875
#Sta/Elev= 28
       0  854.68     9.8  854.08    19.6  853.49    29.4  853.06    39.1  852.83
    48.9  852.67    58.7  852.51    68.5  852.07    78.3  851.01      87  849.94
    88.1  849.81    97.8  849.27     102  849.68   107.6  850.22   117.4  852.02
   127.2   853.4     137  853.88   146.8  854.14   156.6  853.98   166.4  854.22
   176.1  854.54   185.9   855.1   195.7  855.45   205.5  855.34   215.3  855.32
   225.1  855.76   234.8  856.17   244.6  856.69
#Mann= 3 , 0 , 0
       0     .07       0      87    .045       0     102      .1       0
Bank Sta=87,102
XS Rating Curve= 0 ,0
Exp/Cntr=0.3,0.1

Type RM Length L Ch R = 1 ,4789.5  ,136.8,139.7,139.9
XS GIS Cut Line= 4
     1813581.084      465959.375     1813606.258      465978.472
     1813631.432      466005.382     1813668.758      466066.146
#Sta/Elev= 19
       0  853.66     7.9  853.35    15.8  853.07    23.7   852.7    31.6  851.59
    40.8  849.57    47.2  848.35      50  847.82    59.2  849.02    62.2  850.61
    68.4  853.89    77.4  862.62    86.3  870.18    95.2  876.42   104.1  882.27
     113  888.18   121.9     894   130.8  899.72   139.8  905.28
#Mann= 3 , 0 , 0
       0      .1       0    47.2    .045       0    59.2      .1       0
Bank Sta=47.2,59.2
XS Rating Curve= 0 ,0
Exp/Cntr=0.3,0.1

Type RM Length L Ch R = 1 ,4649.8  ,168.3,166.6,165.7
XS GIS Cut Line= 4
     1813486.466      466044.444     1813497.751      466061.805
     1813519.453      466091.319     1813568.064      466134.722
#Sta/Elev= 16
       0  854.09     6.9  853.31    13.8  851.56    20.7  848.95    29.9   845.5
      39  844.31    44.9  845.63    48.2  846.37    57.3  852.32    66.6  860.35
      76  867.95    85.3  875.01    94.6  881.82   103.9  888.42   113.2   894.8
   122.5  901.01
#Mann= 3 , 0 , 0
       0      .1       0    29.9    .045       0    44.9      .1       0
Bank Sta=29.9,44.9
XS Rating Curve= 0 ,0
Exp/Cntr=0.3,0.1

Type RM Length L Ch R = 1 ,4483.1  ,171.2,172.4,173.5
XS GIS Cut Line= 2
     1813344.105      466136.458     1813410.078      466215.451
#Sta/Elev= 14
       0  848.86     9.4  847.48    18.7  843.49    27.6  839.59    28.1  839.37
    37.4  838.35    42.6  839.39    46.8  840.23    56.1  847.52    65.5  856.91
    74.8  865.18    84.2  872.58    93.6  880.11   102.9  887.42
#Mann= 3 , 0 , 0
       0      .1       0    28.1    .045       0    42.6      .1       0
Bank Sta=28.1,42.6
XS Rating Curve= 0 ,0
Exp/Cntr=0.3,0.1

Type RM Length L Ch R = 1 ,4310.8  ,169.8,169.6,168.9
XS GIS Cut Line= 2
     1813200.008      466226.736       1813257.3      466303.125
#Sta/Elev= 15
       0  844.12     9.6  842.86    19.1  839.25   25.95  836.81    28.6  835.79
    28.8  835.79    38.2  836.02   41.81  837.88    43.8  838.84    47.7  840.81
    57.3  849.08    66.8  857.92    76.4  865.93    85.9  873.73    95.5  881.35
#Mann= 3 , 0 , 0
       0      .1       0   25.95    .045       0   41.81      .1       0
Bank Sta=25.95,41.81
XS Rating Curve= 0 ,0
Exp/Cntr=0.3,0.1

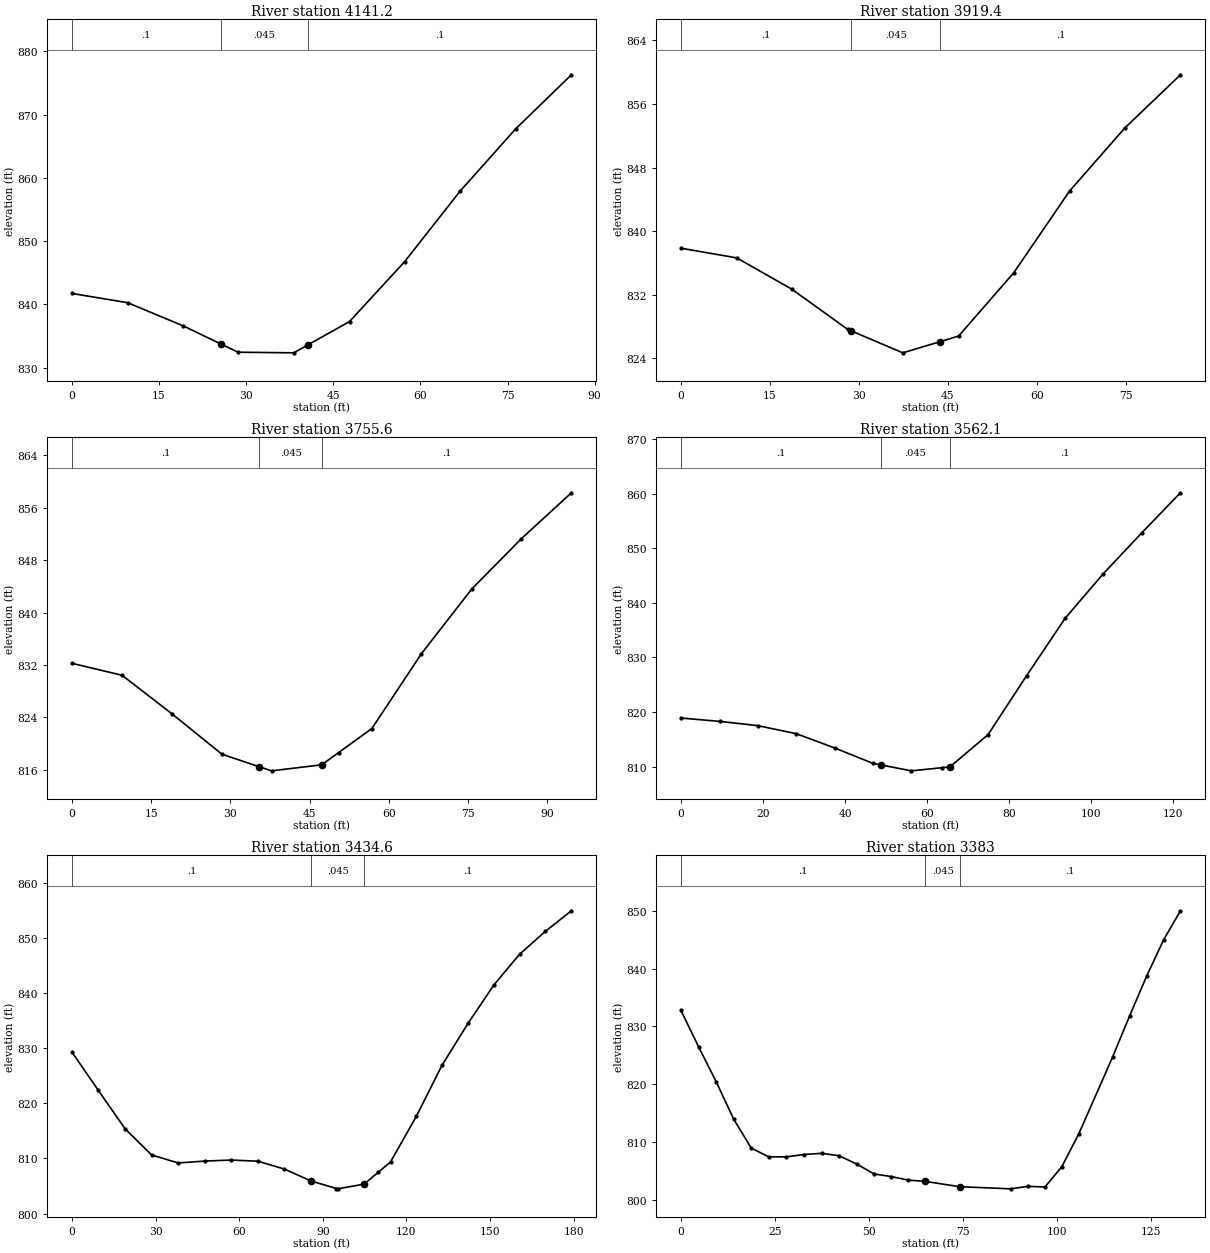
Type RM Length L Ch R = 1 ,4141.2  ,223,221.8,219.9
XS GIS Cut Line= 2
       1813069.8      466336.111     1813122.751      466403.819
#Sta/Elev= 12
       0  841.74     9.6  840.28    19.1  836.64    25.6  833.78    28.6  832.46
    38.2  832.36    40.6   833.6    47.8  837.31    57.3  846.78    66.8  857.87
    76.4  867.74      86  876.29
#Mann= 3 , 0 , 0
       0      .1       0    25.6    .045       0    40.6      .1       0
Bank Sta=25.6,40.6
XS Rating Curve= 0 ,0
Exp/Cntr=0.3,0.1

Type RM Length L Ch R = 1 ,3919.4  ,163.8,163.8,163.2
XS GIS Cut Line= 2
     1812896.189      466476.736     1812952.612      466539.236
#Sta/Elev= 12
       0  837.87     9.4  836.65    18.7  832.71    28.1  827.66    28.7  827.47
    37.4  824.71    43.7  826.12    46.8  826.82    56.1  834.78    65.5  845.05
    74.8  852.97    84.2  859.68
#Mann= 3 , 0 , 0
       0      .1       0    28.7    .045       0    43.7      .1       0
Bank Sta=28.7,43.7
XS Rating Curve= 0 ,0
Exp/Cntr=0.3,0.1

Type RM Length L Ch R = 1 ,3755.6  ,195.8,193.5,191.3
XS GIS Cut Line= 2
     1812784.209      466591.319     1812848.446      466660.764
#Sta/Elev= 13
       0  832.25     9.5  830.42    18.9  824.57    28.4  818.38    35.5  816.46
    37.8  815.84    47.3  816.76    50.5  818.62    56.8  822.29    66.2  833.72
    75.7  843.56    85.1  851.25    94.6  858.27
#Mann= 3 , 0 , 0
       0      .1       0    35.5    .045       0    47.3      .1       0
Bank Sta=35.5,47.3
XS Rating Curve= 0 ,0
Exp/Cntr=0.3,0.1

Type RM Length L Ch R = 1 ,3562.1  ,127.9,127.5,133
XS GIS Cut Line= 2
     1812640.112      466727.604     1812731.258      466808.333
#Sta/Elev= 16
       0  818.89     9.4  818.28    18.7   817.5    28.1  816.02    37.5   813.4
    46.8  810.58    48.7   810.3    56.2  809.21    63.7  809.79    65.6  809.94
    74.9  815.86    84.3  826.67    93.7  837.19     103  845.35   112.4  852.86
   121.8  860.18
#Mann= 3 , 0 , 0
       0      .1       0    48.7    .045       0    65.6      .1       0
Bank Sta=48.7,65.6
XS Rating Curve= 0 ,0
Exp/Cntr=0.3,0.1

Type RM Length L Ch R = 1 ,3434.6  ,18,51.7,104.3
XS GIS Cut Line= 3
     1812493.237       466747.44     1812578.307      466823.829
     1812600.876      466884.593
#Sta/Elev= 22
       0  829.31     9.5  822.34    19.1  815.36    28.6  810.63    38.1  809.18
    47.6  809.52    57.2  809.71    66.7   809.5    76.2  808.07    85.8   805.9
    94.9  804.54    95.3  804.48   104.8  805.33   109.9  807.49   114.3  809.36
   123.6  817.68   132.8  826.95   142.1  834.52   151.4  841.52   160.6  847.08
   169.9  851.26   179.2  854.98
#Mann= 3 , 0 , 0
       0      .1       0    85.8    .045       0   104.8      .1       0
Bank Sta=85.8,104.8
XS Rating Curve= 0 ,0
Exp/Cntr=0.3,0.1

Type RM Length L Ch R = 1 ,3383    ,64,75.3,64.4
XS GIS Cut Line= 4
     1812462.161       466760.59     1812548.098      466817.014
     1812486.466      466883.854     1812544.626      466926.389
#Sta/Elev= 26
       0  832.75     4.7  826.45    9.35  820.46      14     814    18.7  808.97
   23.35  807.46   28.05  807.46    32.7  807.86    37.4  808.07   42.05  807.65
   46.75  806.22    51.4   804.5   55.95  804.05    60.5  803.44   65.05  803.21
   74.15   802.3   87.75  801.93    92.3  802.36   96.85  802.25  101.35  805.78
  105.85  811.43   114.9  824.78   119.4  831.86   123.9  838.68   128.4  844.93
   132.9  849.98
#Mann= 3 , 0 , 0
       0      .1       0   65.05    .045       0   74.15      .1       0
Bank Sta=65.05,74.15
XS Rating Curve= 0 ,0
Skew Angle= 60
Exp/Cntr=0.3,0.1