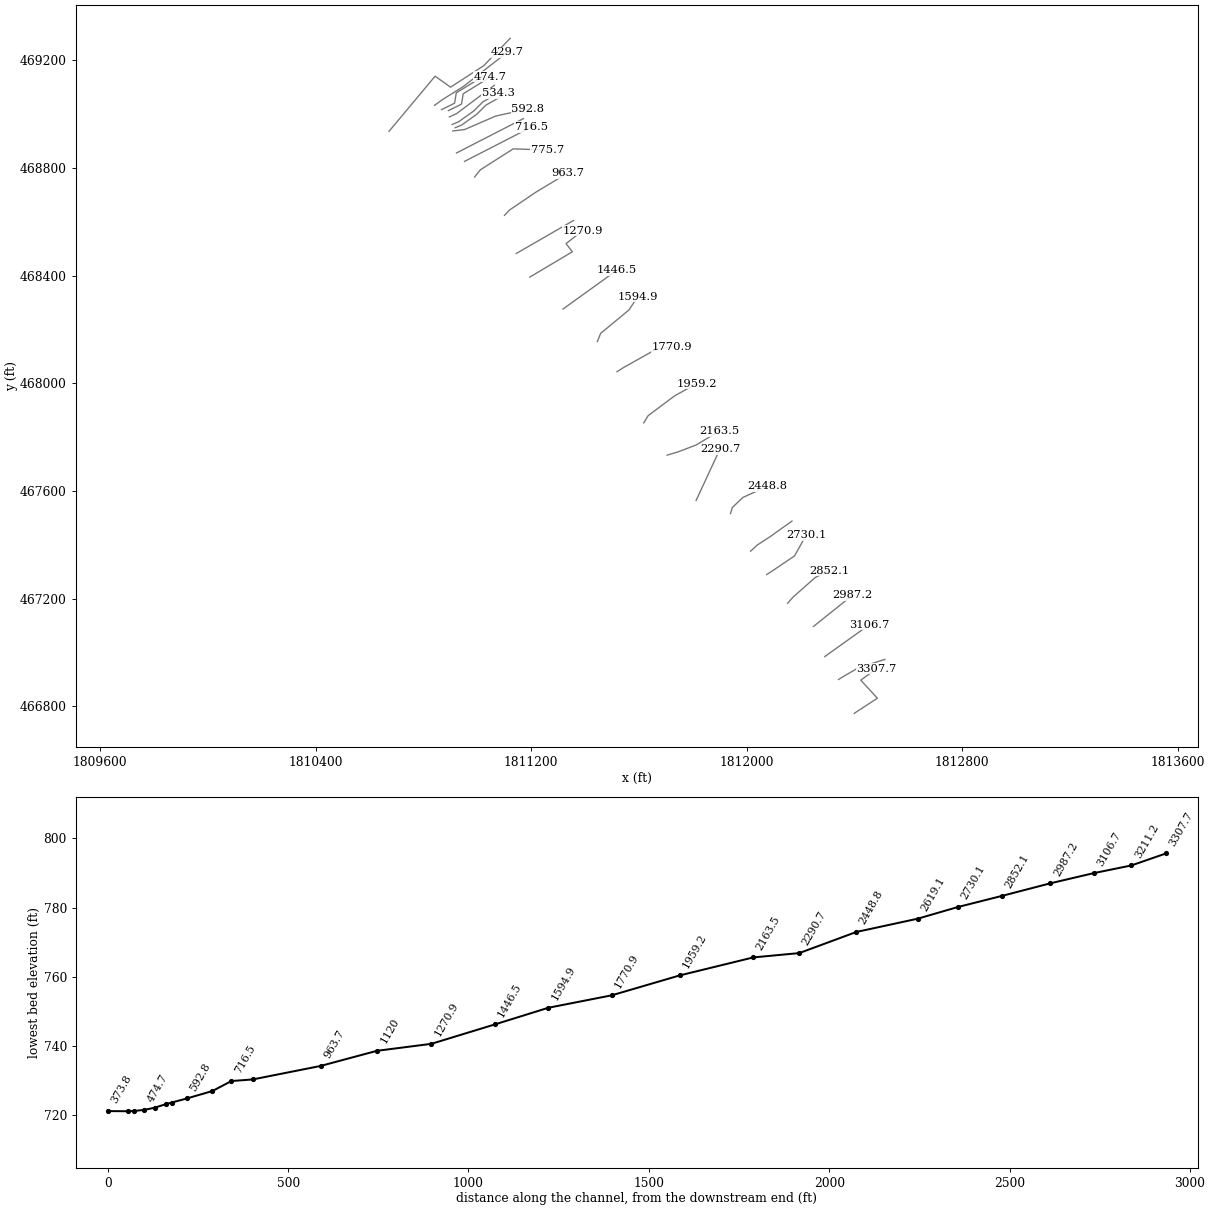
HEC-RAS study GEORGESCK.prj: GEORGESCK

--- GEORGESCK.g01 (geometry) --- (continued)

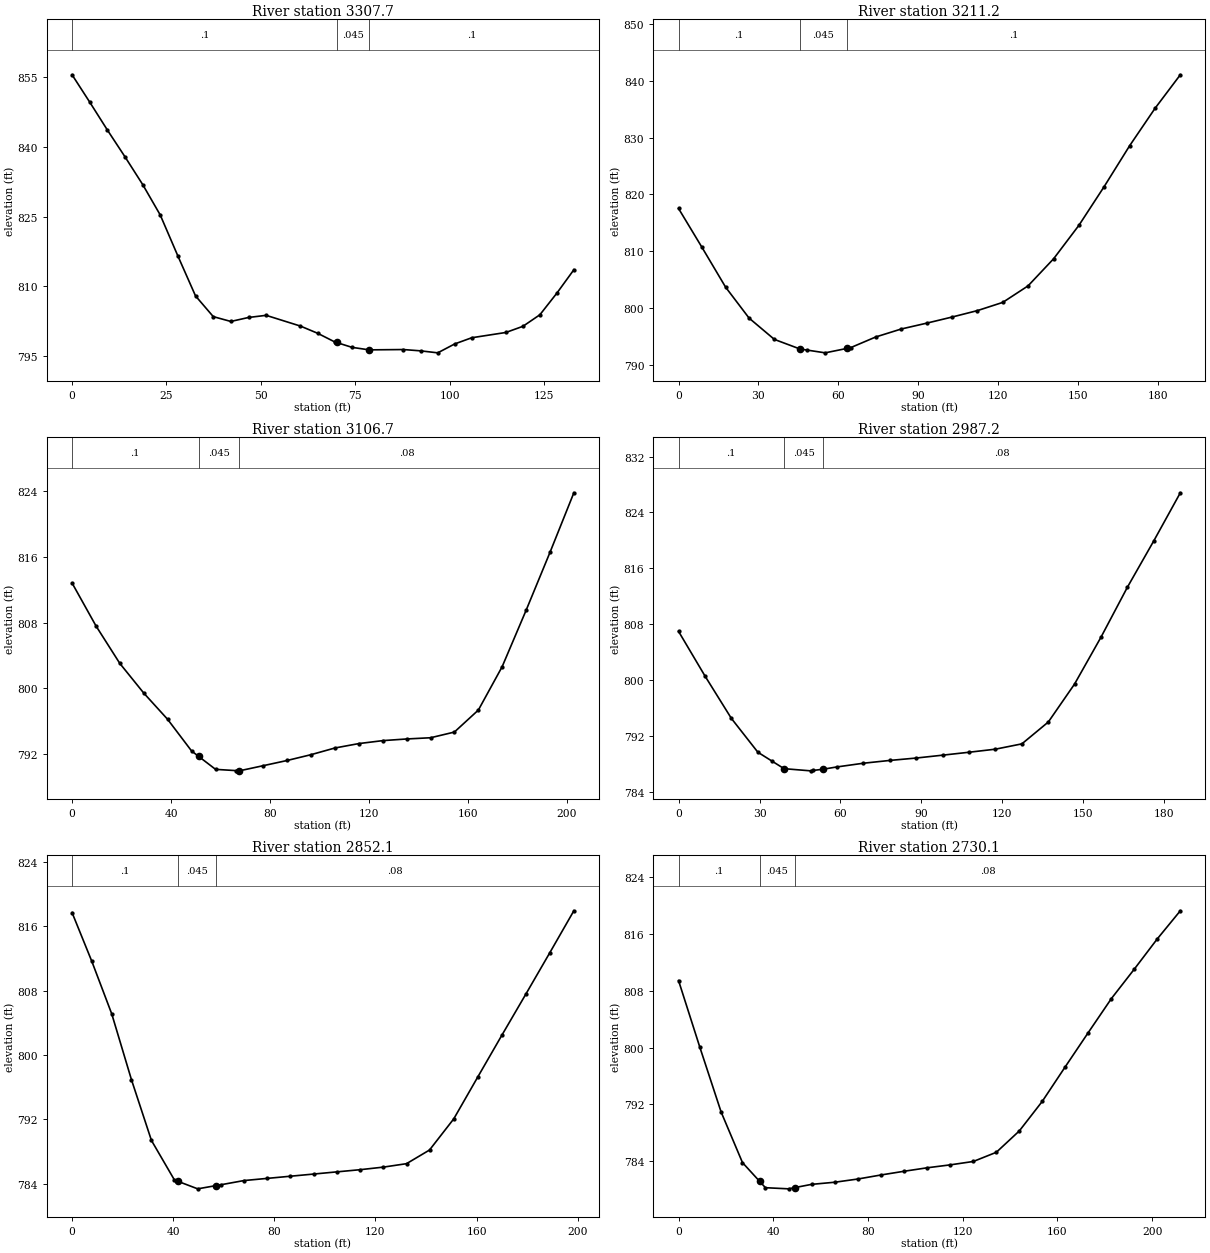
Type RM Length L Ch R = 1 ,3307.7  ,146.3,96.5,43.3
XS GIS Cut Line= 4
     1812398.793      466773.611      1812484.73      466830.034
     1812423.098      466896.875     1812481.258      466939.409
#Sta/Elev= 28
       0  855.58     4.7  849.66    9.35  843.68      14  837.93    18.7  831.94
   23.35  825.38   28.05   816.5    32.7  807.94    37.4  803.48   42.05  802.44
   46.75   803.3    51.4  803.76    60.5  801.44   65.05  799.89    69.6  798.02
   70.05  797.91   74.15  796.86    78.7  796.32   87.75  796.39    92.3  796.11
   96.85  795.68  101.35   797.6  105.85  798.93   114.9  800.07   119.4  801.39
   123.9  803.88   128.4  808.54   132.9  813.58
#Mann= 3 , 0 , 0
       0      .1       0   70.05    .045       0    78.7      .1       0
Bank Sta=70.05,78.7
XS Rating Curve= 0 ,0
Skew Angle= 60
Exp/Cntr=0.3,0.1

Type RM Length L Ch R = 1 ,3211.2  ,102,104.5,106.4
XS GIS Cut Line= 4
     1812340.633      466899.479     1812363.203      466913.368
     1812412.682      466942.014     1812512.508      466974.132
#Sta/Elev= 23
       0  817.54     8.8  810.72    17.7  803.71    26.5  798.29      36  794.55
    45.6  792.87    48.2  792.68    55.1  792.19    63.2  792.96    64.6  793.09
    74.1  794.98    83.7  796.38    93.2   797.4   102.7  798.47   112.3  799.61
   121.8  801.05   131.3  803.95   140.9  808.71   150.4  814.58   159.9  821.39
   169.5  828.59     179  835.13   188.5  841.02
#Mann= 3 , 0 , 0
       0      .1       0    45.6    .045       0    63.2      .1       0
Bank Sta=45.6,63.2
XS Rating Curve= 0 ,0
Exp/Cntr=0.3,0.1

Type RM Length L Ch R = 1 ,3106.7  ,118.3,119.5,120.8
XS GIS Cut Line= 2
     1812289.418      466984.548     1812454.348      467102.604
#Sta/Elev= 24
       0  812.83     9.7  807.59    19.3  803.04      29  799.42    38.6  796.24
    48.3  792.38    51.1  791.73      58  790.14    66.1  789.99    67.6  789.96
    77.3  790.59    86.9  791.22    96.6  791.93   106.2  792.74   115.9  793.28
   125.6  793.64   135.2  793.84   144.9  793.99   154.5  794.68   164.2  797.36
   173.8  802.63   183.5  809.51   193.2   816.6   202.8  823.82
#Mann= 3 , 0 , 0
       0      .1       0    51.1    .045       0    67.6     .08       0
Bank Sta=51.1,67.6
XS Rating Curve= 0 ,0
Exp/Cntr=0.3,0.1

Type RM Length L Ch R = 1 ,2987.2  ,133.4,135.1,136.1
XS GIS Cut Line= 2
     1812247.751      467096.527     1812392.716      467212.847
#Sta/Elev= 23
       0  806.99     9.8   800.6    19.6  794.52    29.4  789.69    34.8  788.38
    39.1  787.34    48.9  787.03    49.8  787.08   53.68  787.27    58.7  787.59
    68.5  788.12    78.3  788.52      88  788.86    97.8  789.27   107.6  789.69
   117.4  790.13   127.2  790.89     137  794.02   146.7  799.44   156.5  806.15
   166.3  813.31   176.1  819.96   185.9  826.82
#Mann= 3 , 0 , 0
       0      .1       0    39.1    .045       0   53.68     .08       0
Bank Sta=39.1,53.68
XS Rating Curve= 0 ,0
Exp/Cntr=0.3,0.1

Type RM Length L Ch R = 1 ,2852.1  ,125.4,122.1,119
XS GIS Cut Line= 4
     1812151.397      467182.465      1812172.23      467205.902
     1812254.696      467278.819     1812305.911      467303.993
#Sta/Elev= 25
       0  817.72     7.8  811.67    15.7  805.12    23.5  796.93    31.4  789.38
    40.5  784.46    41.9  784.29    49.7  783.36    56.9  783.76    58.9  783.87
      68  784.39    77.2  784.66    86.4  784.93    95.6   785.2   104.7  785.47
   113.9  785.74   123.1  786.06   132.3  786.49   141.4  788.19     151  792.07
   160.5  797.28     170  802.46   179.5  807.58     189  812.74   198.5  817.95
#Mann= 3 , 0 , 0
       0      .1       0    41.9    .045       0    56.9     .08       0
Bank Sta=41.9,56.9
XS Rating Curve= 0 ,0
Exp/Cntr=0.3,0.1

Type RM Length L Ch R = 1 ,2730.1  ,110.1,111,110.6
XS GIS Cut Line= 4
      1812074.14      467289.236     1812096.709      467303.993
     1812177.439       467358.68     1812219.973      467435.069
#Sta/Elev= 25
       0  809.43       9  800.05      18  790.93      27  783.83    34.2  781.21
    36.7   780.3    46.5  780.14    49.2  780.32    56.2  780.77      66  781.07
    75.7  781.52    85.5  782.09    95.2  782.61     105   783.1   114.7  783.51
   124.5  783.99   134.2  785.28   143.9  788.28   153.6  792.44   163.3   797.3
     173   802.1   182.8   806.9   192.5  811.05   202.2   815.3   211.9  819.24
#Mann= 3 , 0 , 0
       0      .1       0    34.2    .045       0    49.2     .08       0
Bank Sta=34.2,49.2
XS Rating Curve= 0 ,0
Exp/Cntr=0.3,0.1

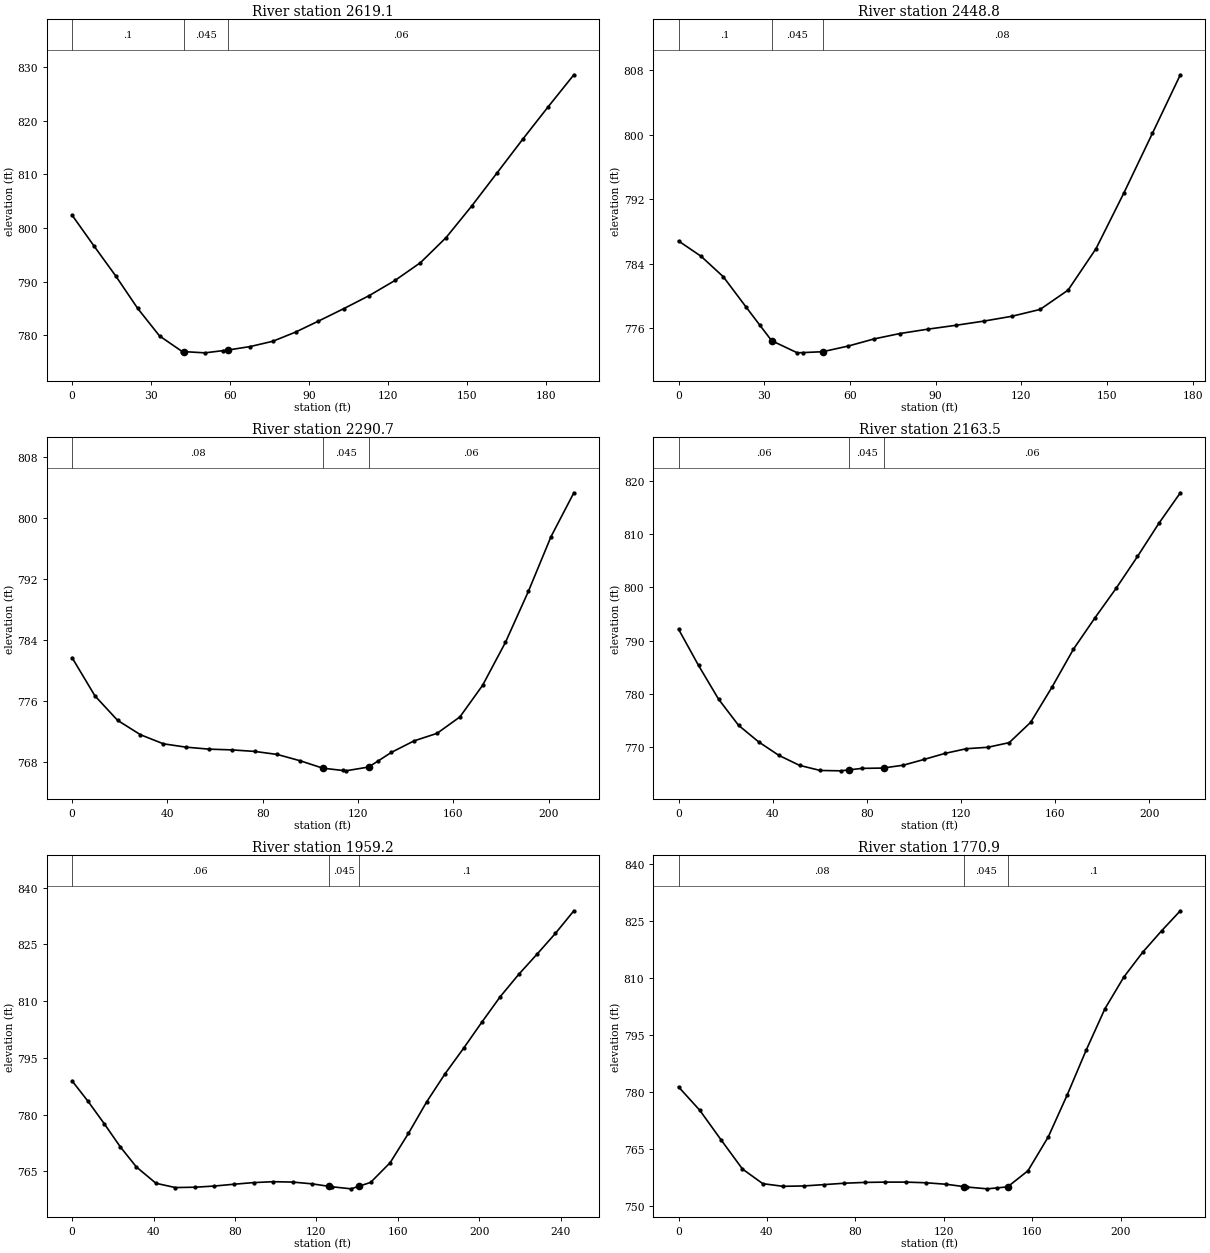
Type RM Length L Ch R = 1 ,2619.1  ,161.4,170.3,174.5
XS GIS Cut Line= 4
     1812014.244      467376.041      1812038.55      467398.611
     1812088.897      467431.597      1812167.89      467488.021
#Sta/Elev= 24
       0  802.41     8.3  796.68    16.6  791.06    24.9  785.04    33.2  779.91
    41.8  777.01    42.3     777    50.4  776.77    57.3  777.18      59  777.28
    67.6  777.94    76.2  778.93    84.8  780.63    93.4  782.66   103.1     785
   112.8  787.44   122.5  790.24   132.2  793.56   141.9  798.22   151.6  804.08
   161.3   810.3     171  816.54   180.7  822.61   190.4  828.54
#Mann= 3 , 0 , 0
       0      .1       0    42.3    .045       0      59     .06       0
Bank Sta=42.3,59
XS Rating Curve= 0 ,0
Exp/Cntr=0.3,0.1

Type RM Length L Ch R = 1 ,2448.8  ,154.4,158.1,167
XS GIS Cut Line= 4
     1811939.591      467515.798     1811946.536      467538.368
     1811985.425      467575.565     1812074.834      467616.364
#Sta/Elev= 22
       0  786.81     7.9  784.91    15.7  782.36    23.6  778.63    28.5  776.34
    32.6  774.43    41.6  772.92    43.5  772.95    50.5  773.06    59.5  773.77
    68.5  774.65    77.4  775.31    87.3  775.86    97.1  776.34   106.9  776.86
   116.7  777.46   126.6  778.31   136.4  780.71   146.2  785.87     156  792.82
   165.9  800.16   175.7  807.45
#Mann= 3 , 0 , 0
       0      .1       0    32.6    .045       0    50.5     .08       0
Bank Sta=32.6,50.5
XS Rating Curve= 0 ,0
Exp/Cntr=0.3,0.1

Type RM Length L Ch R = 1 ,2290.7  ,145,127.2,109.3
XS GIS Cut Line= 2
     1811811.987      467564.409     1811900.529      467755.382
#Sta/Elev= 25
       0  781.67     9.6  776.65    19.1  773.44    28.7  771.55    38.3  770.36
    47.8  769.92    57.4  769.66      67  769.56    76.6  769.36    86.1  768.96
    95.7  768.13   105.2  767.16   113.5  766.86   114.8  766.81   124.4  767.31
   128.5  768.13     134  769.24   143.5  770.75   153.1  771.73   162.7  773.89
   172.2  778.03   181.8  783.68   191.4  790.36   200.9  797.55   210.5  803.32
#Mann= 3 , 0 , 0
       0     .08       0   105.2    .045       0   124.4     .06       0
Bank Sta=105.2,124.4
XS Rating Curve= 0 ,0
Exp/Cntr=0.3,0.1

Type RM Length L Ch R = 1 ,2163.5  ,197,204.3,210.1
XS GIS Cut Line= 4
     1811704.348      467732.812     1811745.147      467744.965
     1811811.119      467770.139     1811897.057      467821.354
#Sta/Elev= 27
       0  792.13     8.5  785.33      17  779.01    25.5   774.1    34.1  770.97
    42.6  768.47    51.4  766.59    60.2  765.63      69  765.56    72.4  765.74
    77.9  766.02    86.7  766.08    87.4  766.12    95.5  766.62   104.4  767.71
   113.2  768.83   122.3  769.71   131.4  769.98   140.5  770.85   149.6  774.66
   158.7  781.28   167.8  788.39   176.8  794.18   185.9  799.79     195  805.77
   204.1     812   213.2  817.72
#Mann= 3 , 0 , 0
       0     .06       0    72.4    .045       0    87.4     .06       0
Bank Sta=72.4,87.4
XS Rating Curve= 0 ,0
Exp/Cntr=0.3,0.1

Type RM Length L Ch R = 1 ,1959.2  ,191.2,188.3,185.5
XS GIS Cut Line= 4
     1811617.543      467852.604     1811634.036      467879.514
     1811733.862      467954.166     1811812.855      467997.569
#Sta/Elev= 30
       0  788.91     7.9  783.46    15.8  777.57    23.7  771.44    31.6  766.12
    41.2  761.81    50.7  760.68    60.3  760.77    69.9  761.08    79.5  761.56
    89.1  761.99    98.7  762.23   108.3  762.13   117.9  761.66     126  761.01
   127.4   760.9     137  760.34     141  761.05   146.6  762.04   156.2  767.26
   165.2  775.04   174.2  783.42   183.2  790.82   192.3  797.57   201.3   804.5
   210.3  811.22   219.3  817.07   228.3  822.42   237.3   827.9   246.4  833.91
#Mann= 3 , 0 , 0
       0     .06       0     126    .045       0     141      .1       0
Bank Sta=126,141
XS Rating Curve= 0 ,0
Exp/Cntr=0.3,0.1

Type RM Length L Ch R = 1 ,1770.9  ,171.4,176,181.2
XS GIS Cut Line= 4
     1811518.584      468042.708      1811542.89      468058.333
      1811663.55      468126.041     1811722.578      468134.722
#Sta/Elev= 28
       0   781.4     9.6  775.25    19.3  767.41    28.9   759.8    38.1  755.94
    47.3  755.24    56.6  755.34    65.8  755.69      75  756.06    84.2  756.27
    93.5  756.35   102.7  756.35   111.9  756.18   121.1  755.78   129.2  755.15
   130.4  755.06   139.6  754.58   144.2  754.84   148.8   755.1     158  759.33
   167.2  768.26   175.8  779.35   184.3  791.03   192.8  801.95   201.4  810.33
   209.9  816.83   218.4  822.44   226.9  827.73
#Mann= 3 , 0 , 0
       0     .08       0   129.2    .045       0   148.8      .1       0
Bank Sta=129.2,148.8
XS Rating Curve= 0 ,0
Exp/Cntr=0.3,0.1

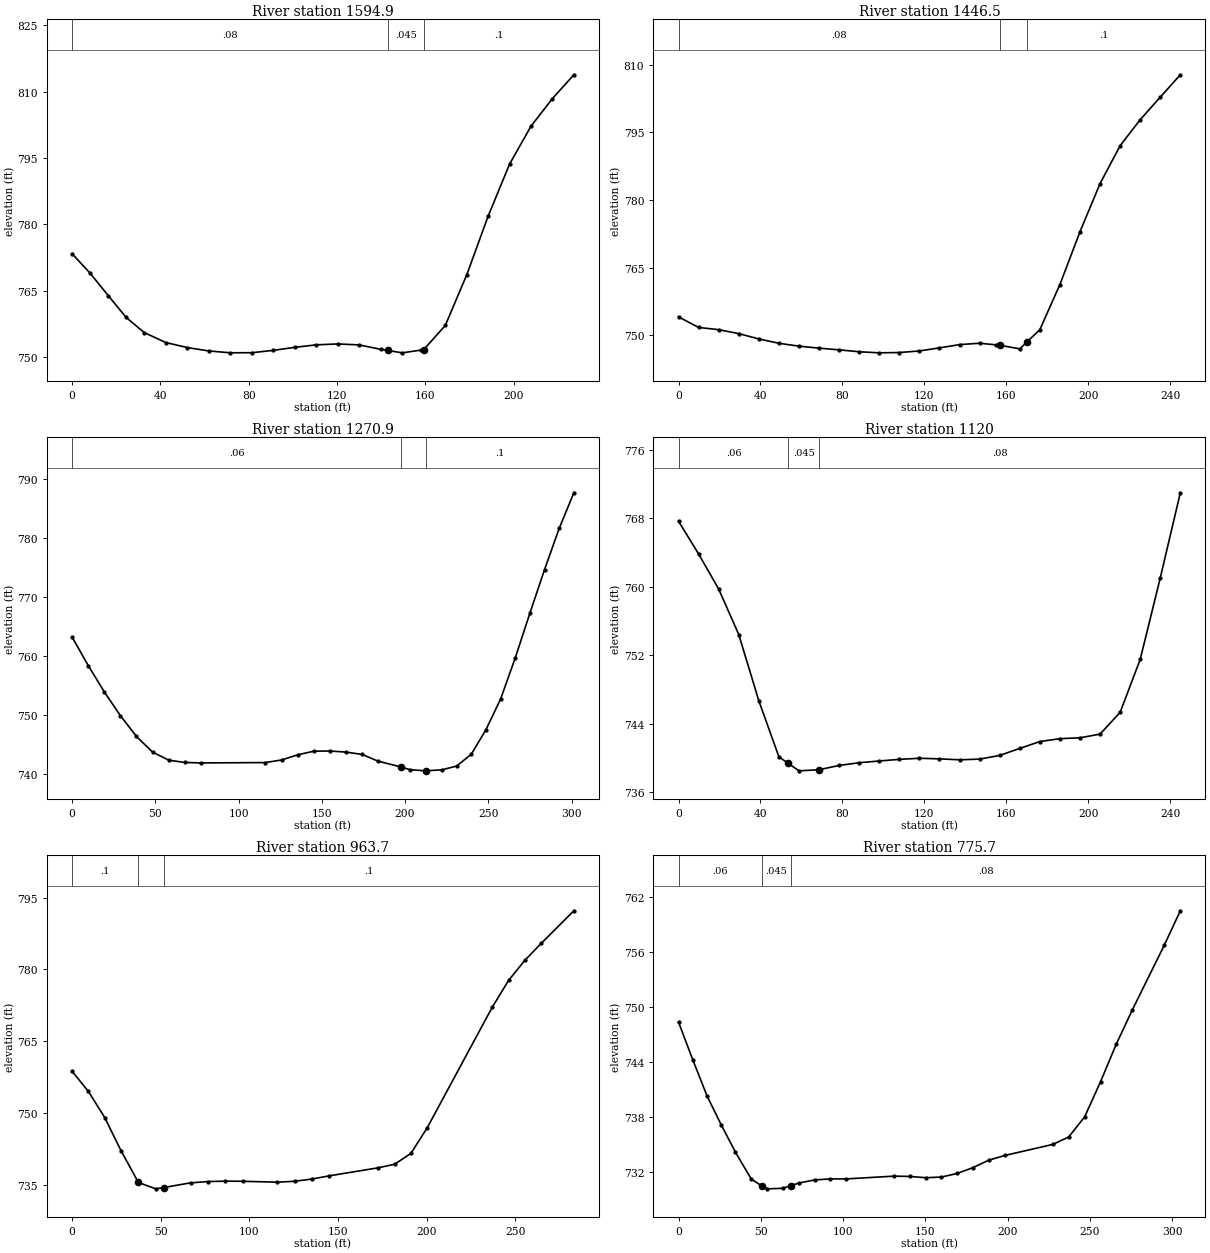
Type RM Length L Ch R = 1 ,1594.9  ,150,148.4,145.2
XS GIS Cut Line= 4
     1811445.668      468154.904     1811457.821      468185.286
     1811562.855      468272.092     1811594.973      468320.703
#Sta/Elev= 27
       0  773.37     8.2  768.94    16.4  763.89    24.5  758.96    32.7  755.54
    42.5  753.29    52.2  752.16    61.9   751.4    71.6  750.98    81.4     751
    91.1  751.53   100.8  752.21   110.6  752.78   120.3  752.98     130  752.76
   139.8  751.76   142.9  751.51   149.5  750.97   157.9  751.58   159.2  751.68
     169  757.17   178.7  768.59   188.4  781.86   198.1  793.61   207.8  802.17
   217.5  808.41   227.2  813.78
#Mann= 3 , 0 , 0
       0     .08       0   142.9    .045       0   159.2      .1       0
Bank Sta=142.9,159.2
XS Rating Curve= 0 ,0
Exp/Cntr=0.3,0.1

Type RM Length L Ch R = 1 ,1446.5  ,154.5,175.7,197.5
XS GIS Cut Line= 2
     1811318.064      468275.564     1811516.848      468418.793
#Sta/Elev= 28
       0  754.11     9.8  751.77    19.6  751.27    29.4   750.4    39.2  749.22
      49  748.26    58.8  747.62    68.6  747.18    78.4   746.8    88.2  746.38
      98  746.14   107.8  746.21   117.6  746.56   127.4  747.24   137.2  747.96
     147  748.27   155.2   747.9   156.8  747.83   166.6  747.02   170.2  748.58
   176.4  751.27   186.2  761.26     196  772.96   205.8  783.61   215.6  792.02
   225.4  797.78   235.2  802.77     245  807.73
#Mann= 3 , 0 , 0
       0     .08       0   156.8    .045       0   170.2      .1       0
Bank Sta=156.8,170.2
XS Rating Curve= 0 ,0
Exp/Cntr=0.3,0.1

Type RM Length L Ch R = 1 ,1270.9  ,173.7,150.9,126.3
XS GIS Cut Line= 4
     1811194.843      468394.142     1811352.786      468488.238
     1811329.348      468518.619     1811391.848      468567.231
#Sta/Elev= 30
       0  763.21     9.7  758.38    19.4  753.89      29   749.9    38.7  746.35
    48.4  743.69    58.1  742.34    67.7  741.95    77.4  741.87   116.1  741.93
   125.8  742.37   135.5  743.24   145.1  743.86   154.8  743.89   164.5  743.71
   174.2  743.31   183.8  742.17   197.4   741.2     203  740.73   212.4  740.53
   222.2  740.71     231  741.34   239.8  743.35   248.6   747.5   257.4   752.7
   266.2  759.67     275  767.26   283.8  774.64   292.6  781.63   301.4  787.65
#Mann= 3 , 0 , 0
       0     .06       0   197.4    .045       0   212.4      .1       0
Bank Sta=197.4,212.4
XS Rating Curve= 0 ,0
Exp/Cntr=0.3,0.1

Type RM Length L Ch R = 1 ,1120    ,153.2,156.3,157.7
XS GIS Cut Line= 2
      1811144.93      468482.032     1811357.126      468604.557
#Sta/Elev= 27
       0  767.68     9.8  763.85    19.6  759.75    29.4  754.44    39.2   746.7
      49  740.15    53.6  739.38    58.8  738.51    68.6  738.64    78.4  739.14
    88.2  739.46      98  739.66   107.8  739.85   117.6  739.98   127.4  739.91
   137.2   739.8     147  739.88   156.8  740.31   166.6  741.13   176.4  741.93
   186.2  742.27     196  742.37   205.8   742.8   215.6  745.34   225.4  751.52
   235.2  761.05     245     771
#Mann= 3 , 0 , 0
       0     .06       0    53.6    .045       0    68.6     .08       0
Bank Sta=53.6,68.6
XS Rating Curve= 0 ,0
Exp/Cntr=0.3,0.1

Type RM Length L Ch R = 1 ,963.7   ,190,188,187.4
XS GIS Cut Line= 4
      1811101.05      468623.654     1811120.147      468643.619
     1811217.369      468709.592     1811335.425      468780.772
#Sta/Elev= 24
       0   758.7     9.2  754.48    18.4  749.03    27.6   742.1    37.4  735.45
    47.2  734.12    51.7  734.39    66.8  735.37    76.6  735.64    86.4  735.73
    96.2   735.7   115.8  735.51   125.5   735.7   135.3  736.17   145.1  736.84
   172.7  738.52   181.9  739.26   191.1  741.52   200.3  746.89     237   772.1
   246.2  777.69   255.4   781.9   264.6  785.42     283  792.24
#Mann= 3 , 0 , 0
       0      .1       0    37.4    .045       0    51.7      .1       0
Bank Sta=37.4,51.7
XS Rating Curve= 0 ,0
Exp/Cntr=0.3,0.1

Type RM Length L Ch R = 1 ,775.7   ,59.3,59.2,58.9
XS GIS Cut Line= 4
     1810989.939      468766.015      1811011.64      468792.925
     1811133.385      468870.507     1811259.253      468866.167
#Sta/Elev= 30
       0  748.34     8.6  744.28    17.3  740.33    25.9  737.19    34.6   734.2
    44.2  731.28   50.53  730.54    53.8  730.22    63.4  730.28    68.3  730.57
    73.1  730.85    82.7  731.19    92.3   731.3   101.9   731.3   130.8   731.6
   140.4  731.57   150.1  731.43   159.7   731.5   169.3  731.89   178.9  732.53
   188.6  733.34   198.3  733.85   227.4  735.05   237.1  735.86   246.8  738.06
   256.4  741.86   266.1     746   275.8   749.7   295.2  756.73   304.9  760.45
#Mann= 3 , 0 , 0
       0     .06       0   50.53    .045       0    68.3     .08       0
Bank Sta=50.53,68.3
XS Rating Curve= 0 ,0
Exp/Cntr=0.3,0.1

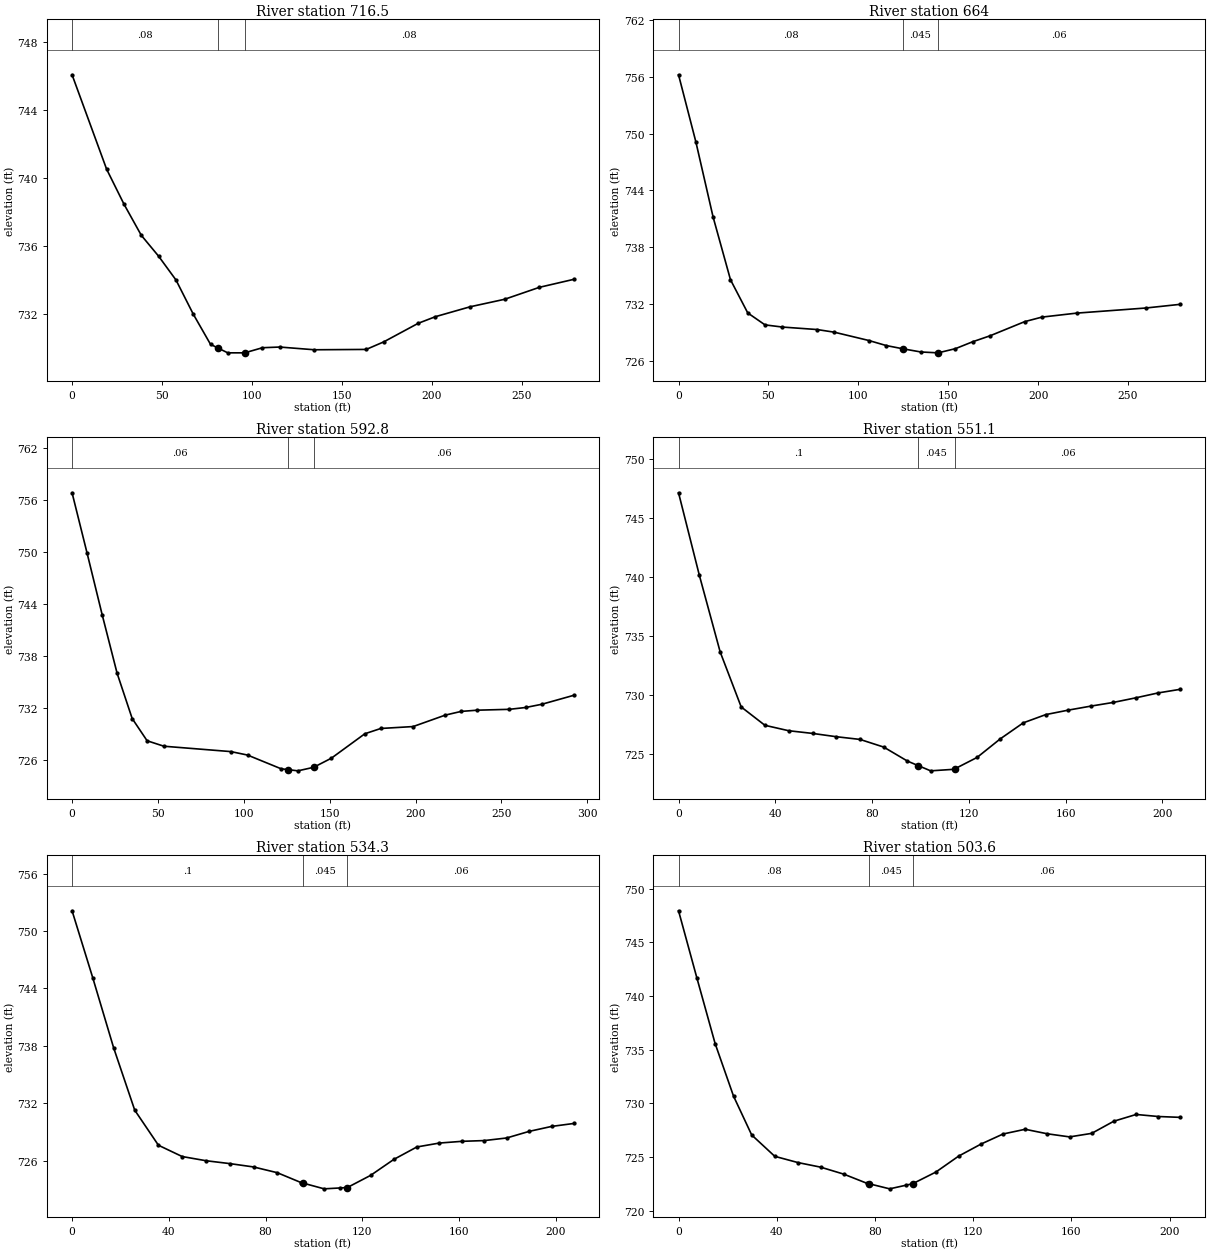
Type RM Length L Ch R = 1 ,716.5   ,51.3,52.4,57.6
XS GIS Cut Line= 2
     1810952.612      468823.958     1811200.876      468951.562
#Sta/Elev= 22
       0  746.05    19.2  740.52    28.9  738.46    38.5  736.64    48.1  735.42
    57.8  734.02    67.4  732.02      77  730.25      81  730.04    86.6  729.75
      96  729.75   105.9  730.05   115.5  730.09   134.8  729.93   163.6  729.95
   173.3  730.39   192.5  731.48   202.1  731.87   221.4  732.45   240.6  732.89
   259.9  733.59   279.1  734.06
#Mann= 3 , 0 , 0
       0     .08       0      81    .045       0      96     .08       0
Bank Sta=81,96
XS Rating Curve= 0 ,0
Exp/Cntr=0.3,0.1

Type RM Length L Ch R = 1 ,664     ,76.4,71.2,62.7
XS GIS Cut Line= 2
     1810923.098      468855.425     1811171.362      468983.029
#Sta/Elev= 22
       0  756.21     9.6  749.16    19.2  741.22    28.9  734.58    38.5  731.08
    48.1  729.82    57.8  729.59      77  729.33    86.6  729.05   105.9  728.17
   115.5  727.64   124.7   727.3   134.8  726.96   144.4  726.87     154  727.31
   163.6  728.04   173.3  728.67   192.5  730.16   202.1  730.64   221.4  731.06
   259.9   731.6   279.1  731.99
#Mann= 3 , 0 , 0
       0     .08       0   124.7    .045       0   144.4     .06       0
Bank Sta=124.7,144.4
XS Rating Curve= 0 ,0
Exp/Cntr=0.3,0.1

Type RM Length L Ch R = 1 ,592.8   ,33.1,41.7,51
XS GIS Cut Line= 4
     1810909.209      468937.022     1810952.612      468942.231
     1811068.932      468992.578     1811187.855      469018.619
#Sta/Elev= 24
       0  756.79     8.7  749.86    17.5  742.74    26.2  735.98      35  730.74
    43.7  728.17    53.5  727.54    92.5  726.92   102.2  726.52   121.7  724.94
   125.7  724.84   131.5   724.7   140.7  725.11     151  726.16   170.5  728.98
   179.8  729.59   198.6  729.81   217.3  731.13   226.6  731.56     236   731.7
   254.7   731.8   264.1  732.01   273.5  732.38   292.2  733.42
#Mann= 3 , 0 , 0
       0     .06       0   125.7    .045       0   140.7     .06       0
Bank Sta=125.7,140.7
XS Rating Curve= 0 ,0
Exp/Cntr=0.3,0.1

Type RM Length L Ch R = 1 ,551.1   ,17.6,16.8,16.9
XS GIS Cut Line= 5
     1810918.107      468949.067     1810941.979      468959.049
     1810997.968       468998.98     1811031.822      469032.834
     1811088.246      469064.952
#Sta/Elev= 25
       0  747.17     8.6  740.16    17.2  733.65    25.9  728.97    35.7  727.41
    45.5  726.95    55.4  726.72    65.2  726.44      75  726.21    84.8  725.56
    94.6  724.37    99.1  723.98   104.2  723.54   113.8  723.67   114.1   723.7
   123.4  724.68     133  726.26   142.5  727.62   151.8  728.32   161.1   728.7
   170.4  729.04   179.6  729.35   188.9  729.74   198.2  730.16   207.4  730.47
#Mann= 3 , 0 , 0
       0      .1       0    99.1    .045       0   114.1     .06       0
Bank Sta=99.1,114.1
XS Rating Curve= 0 ,0
Exp/Cntr=0.3,0.1

Type RM Length L Ch R = 1 ,534.3   ,31.8,30.7,27.6
XS GIS Cut Line= 5
     1810906.822      468961.219     1810930.694      468971.202
     1810986.683      469011.132     1811020.538      469044.987
     1811076.961      469077.105
#Sta/Elev= 25
       0  752.13     8.6  745.08    17.2  737.78    25.9  731.27    35.7   727.6
    45.5  726.42    55.4  725.98    65.2  725.68      75  725.33    84.8  724.73
    94.6   723.7    95.6  723.63   104.2  723.04   110.6  723.13   113.8  723.18
   123.4  724.45     133  726.12   142.5  727.42   151.8  727.83   161.1  728.01
   170.4  728.09   179.6  728.36   188.9  729.05   198.2  729.57   207.4  729.88
#Mann= 3 , 0 , 0
       0      .1       0    95.6    .045       0   113.8     .06       0
Bank Sta=95.6,113.8
XS Rating Curve= 0 ,0
Exp/Cntr=0.3,0.1

Type RM Length L Ch R = 1 ,503.6   ,20.5,28.9,46.1
XS GIS Cut Line= 4
     1810896.362      468989.107     1810923.446      469001.607
     1810990.807      469052.301     1811063.029      469106.468
#Sta/Elev= 26
       0  747.94     7.5  741.66    14.9  735.57    22.4  730.67    29.8  727.05
    39.2  725.06    48.6  724.48    57.9  724.05    67.3   723.4    76.7  722.55
    77.5  722.51      86  722.03    92.5  722.36    95.4  722.51   104.8  723.59
   114.1  725.08   123.2   726.2   132.2  727.14   141.2  727.58   150.2  727.16
   159.3  726.87   168.3   727.2   177.3  728.33   186.4  728.96   195.4  728.77
   204.4  728.69
#Mann= 3 , 0 , 0
       0     .08       0    77.5    .045       0    95.4     .06       0
Bank Sta=77.5,95.4
XS Rating Curve= 0 ,0
Exp/Cntr=0.3,0.1

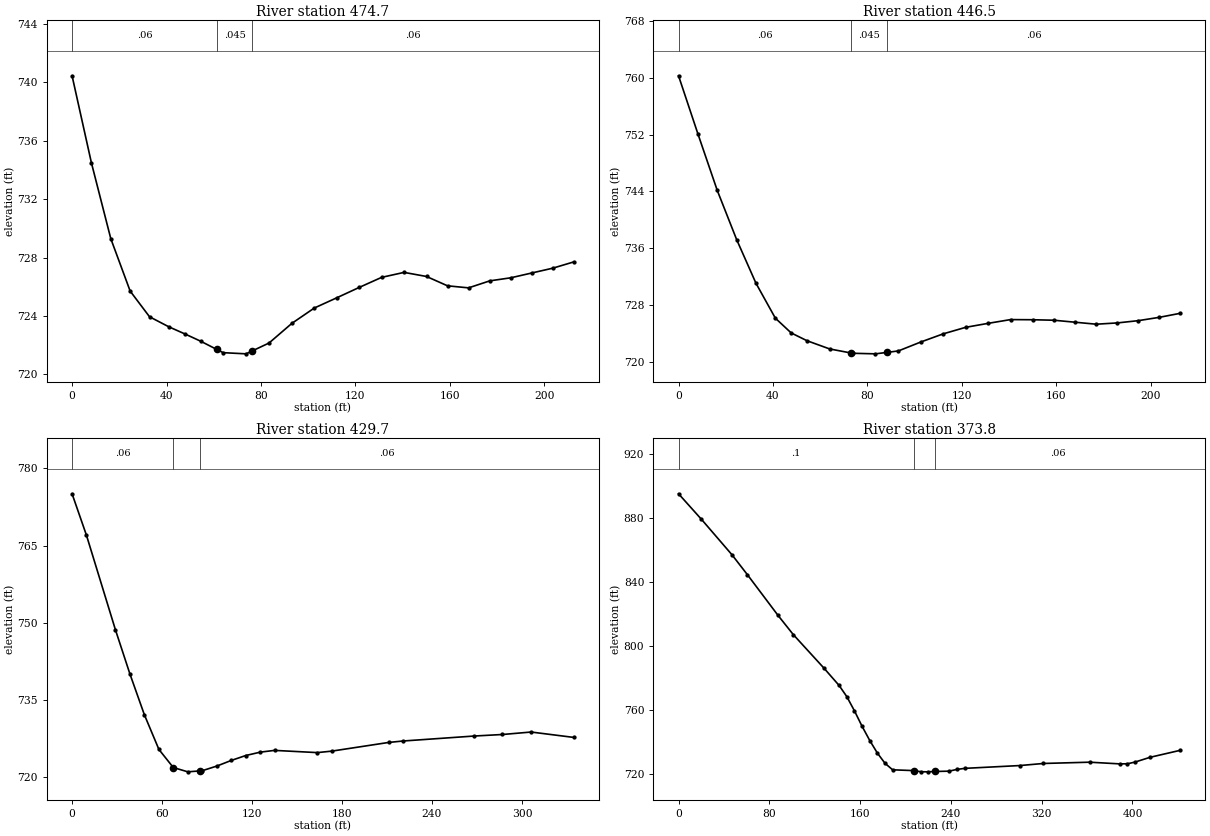
Type RM Length L Ch R = 1 ,474.7   ,17.9,28.2,18.8
XS GIS Cut Line= 6
      1810892.89      469012.718     1810929.696      469030.774
     1810941.501      469037.024     1810947.751      469075.218
     1810996.362      469105.079      1811049.14      469138.413
#Sta/Elev= 27
       0  740.45     8.2  734.48    16.4  729.29    24.6   725.7    32.8  723.94
      41  723.25    47.7  722.77    54.4  722.27    61.3   721.7      64  721.48
    73.7   721.4    76.3   721.6    83.4  722.14    93.1  723.49   102.6  724.54
   112.1  725.24   121.6  725.95   131.1  726.64   140.6  726.98   150.1   726.7
     159  726.06   167.9  725.92   176.9   726.4   185.8  726.61   194.7  726.94
   203.6  727.27   212.5   727.7
#Mann= 3 , 0 , 0
       0     .06       0    61.3    .045       0    76.3     .06       0
Bank Sta=61.3,76.3
XS Rating Curve= 0 ,0
Exp/Cntr=0.3,0.1

Type RM Length L Ch R = 1 ,446.5   ,37.3,16.8,6.5
XS GIS Cut Line= 6
     1810867.196       469016.19     1810904.001      469034.246
     1810915.807      469040.496     1810922.057       469078.69
     1810970.668      469108.551     1811023.446      469141.885
#Sta/Elev= 27
       0  760.31     8.2  752.12    16.4  744.14    24.6  737.21    32.8  731.04
      41  726.12    47.7  724.04    54.4  722.94      64  721.78    73.2   721.2
    73.7  721.17    83.4  721.09    88.2  721.29    93.1   721.5   102.6  722.76
   112.1  723.91   121.6  724.83   131.1  725.39   140.6  725.92   150.1   725.9
     159  725.83   167.9  725.55   176.9  725.27   185.8  725.45   194.7  725.77
   203.6  726.24   212.5  726.81
#Mann= 3 , 0 , 0
       0     .06       0    73.2    .045       0    88.2     .06       0
Bank Sta=73.2,88.2
XS Rating Curve= 0 ,0
Exp/Cntr=0.3,0.1

Type RM Length L Ch R = 1 ,429.7   ,90,55.9,24.5
XS GIS Cut Line= 4
     1810841.545      469032.313     1810872.795      469054.882
     1810946.579      469100.889      1811111.51      469229.362
#Sta/Elev= 23
       0  775.07     9.6     767    28.9  748.64    38.6  740.02    48.2  732.12
    57.9  725.37    67.5  721.85    77.2  721.01      85  721.19    86.9  721.24
    96.5  722.13   106.2  723.23   115.8  724.18   125.5  724.84     135  725.18
   163.5  724.75     173  725.03     211  726.72   220.5     727     268  727.97
     287  728.27   306.1  728.75   334.6   727.7
#Mann= 3 , 0 , 0
       0     .06       0    67.5    .045       0      85     .06       0
Bank Sta=67.5,85
XS Rating Curve= 0 ,0
Exp/Cntr=0.3,0.1

Type RM Length L Ch R = 1 ,373.8   ,25.1,59.8,52.3
XS GIS Cut Line= 5
     1810672.447      468935.612     1810843.454      469140.473
     1810900.746      469099.674      1811024.01      469179.535
       1811122.1      469281.098
#Sta/Elev= 30
       0  894.88  20.223  878.89  47.164  856.69   60.67  844.31  87.611   818.9
 101.116  806.85 128.057  785.94 141.492  775.05  148.28  768.06 154.998  759.19
 161.715  749.54 168.504  740.63 175.221  732.76 181.939  726.39 188.656  722.32
 207.324  721.82 213.546  721.11 219.627  721.05 225.991  721.27 238.436  721.48
 245.366  722.58 252.296  723.23 300.733  724.98 321.521  726.28 362.251  727.08
 388.909  726.02 395.556   726.1 402.202  727.14 415.496  730.14 442.154  734.52
#Mann= 3 , 0 , 0
       0      .1       0 207.324    .045       0 225.991     .06       0
Bank Sta=207.324,225.991
XS Rating Curve= 0 ,0
Skew Angle= 45
Exp/Cntr=0.3,0.1