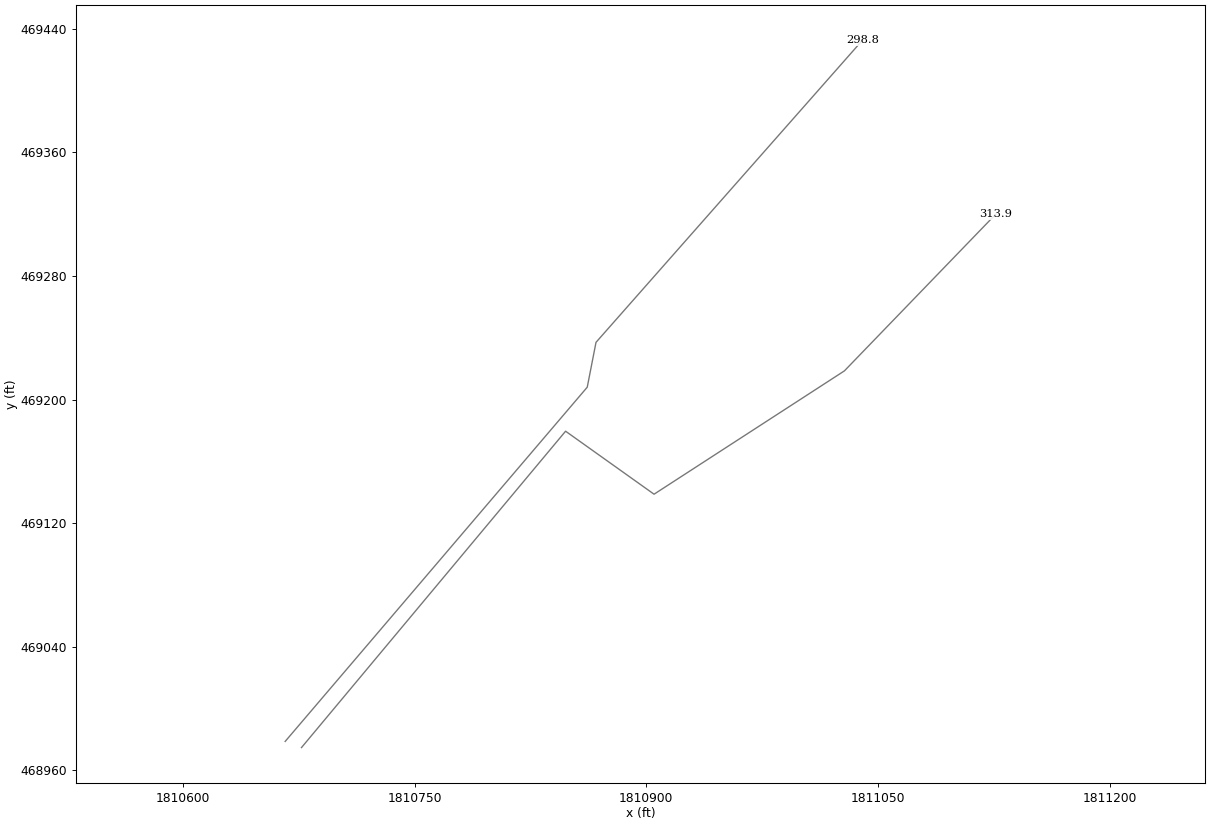
HEC-RAS study GEORGESCK.prj: GEORGESCK

--- GEORGESCK.g01 (geometry) --- (continued)

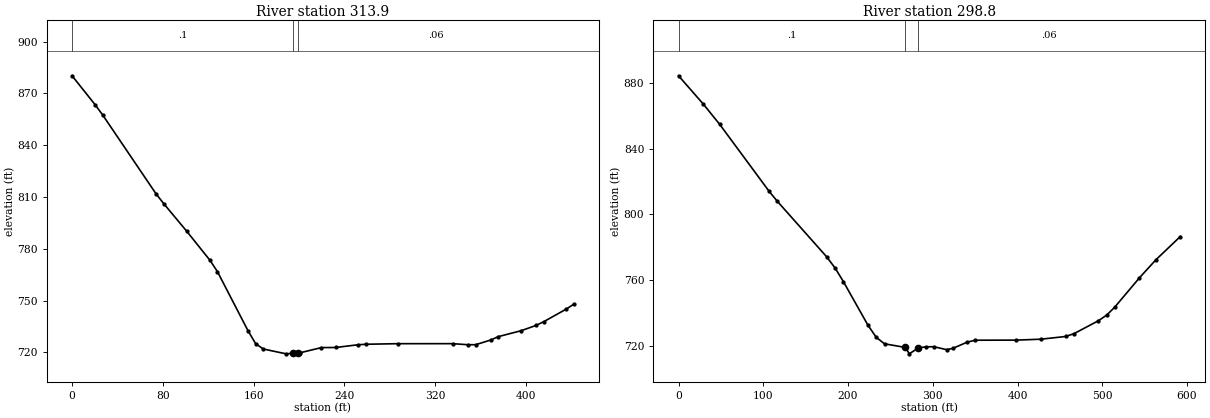
Type RM Length L Ch R = 1 ,313.9   ,8.5,15.2,61.5
XS GIS Cut Line= 5
     1810676.788      468974.674     1810847.795      469179.535
     1810905.086      469138.737      1811028.35      469218.598
      1811126.44       469320.16
#Sta/Elev= 30
       0  880.18  20.223   863.5  26.941  857.53  74.105  811.74  80.893  806.07
 101.116  790.12  121.34  773.52 128.057  766.85 154.998  732.63 161.715  725.16
 168.504  722.01 188.656  719.22 194.879  719.55 198.768  719.75 201.101  719.87
 219.769  722.84 232.214  722.89 252.296   724.5 259.225  724.77 286.873   725.1
 335.381  725.11 348.957  724.49 355.604  724.51 368.898  727.23 375.544  729.18
 395.556  732.59 408.849  735.67 415.496  737.79 435.436  745.11 442.154  747.99
#Mann= 3 , 0 , 0
       0      .1       0 194.879    .045       0 198.768     .06       0
Bank Sta=194.879,198.768
XS Rating Curve= 0 ,0
Skew Angle= 45
Exp/Cntr=0.3,0.1

Type RM Length L Ch R = 1 ,298.8   ,305.8,298.8,291.7
XS GIS Cut Line= 4
     1810666.229      468978.657     1810861.822      469208.026
     1810867.499       469237.07     1811040.186      469432.865
#Sta/Elev= 30
       0  884.18    29.2  867.01    48.6  854.65     107  813.93   116.7  807.86
     175   774.1   184.8  767.35   194.5  759.19   223.6  732.59   233.4  725.27
   243.1  721.38   267.8  719.16   272.3  715.29   282.8  718.84   291.7  719.56
   301.4  719.61   316.2  717.84   323.6  718.59   340.7  722.43   350.4  723.57
   398.7  723.62   427.7  724.19   456.7  725.83   466.4   727.5   495.4  735.37
   505.1  738.77   514.8   743.7   543.8  761.43   563.1  772.33   592.1  786.56
#Mann= 3 , 0 , 0
       0      .1       0   267.8    .045       0   282.8     .06       0
Bank Sta=267.8,282.8
XS Rating Curve= 0 ,0
Exp/Cntr=0.3,0.1

Chan Stop Cuts=-1
Use User Specified Reach Order=0
Composite Channel Slope=5